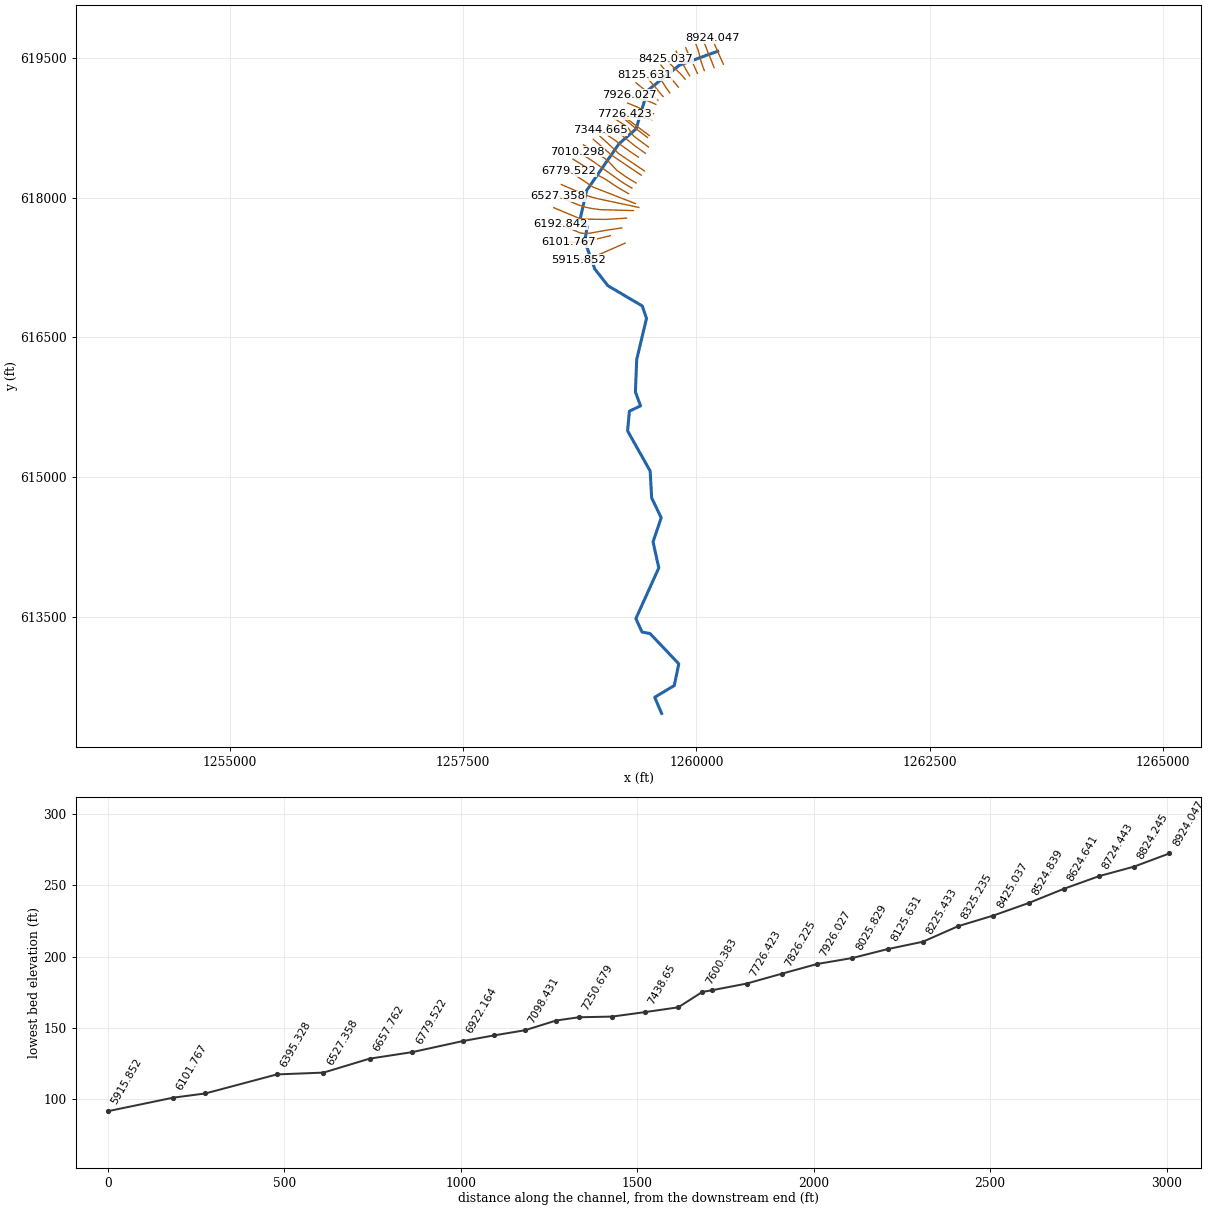
--- 481_ras.prj (project) ---

Proj Title=481
Current Plan=p01
Default Exp/Contr=0.3,0.1
English Units
Geom File=g01
Flow File=f01
Plan File=p01
Y Axis Title=Elevation
X Axis Title(PF)=Main Channel Distance
X Axis Title(XS)=Station
BEGIN DESCRIPTION:
RFD model 481 exported to HEC-RAS
END DESCRIPTION:

--- 481_ras.p01 (plan) ---

Plan Title=Plan 01
Program Version=4.10
Short Identifier=Plan 01
Geom File=g01
Flow File=f01
Subcritical Flow
Calc Critical at every XS
Secant Critical Depth

--- 481_ras.f01 (steady flow) ---

Flow Title=Flow 01
Program Version=5.01
Number of Profiles= 5
Profile Names=10yr,25yr,50yr,100yr,500yr
River Rch & RM=481,53,8924.047
  364.17  431.09  513.04  542.97  630.37
River Rch & RM=481,53,8125.631
  376.31  447.61  533.28  567.14  662.55
River Rch & RM=481,53,7926.027
  385.26  459.83  548.27  585.11   686.6
River Rch & RM=481,53,7826.225
  387.89  463.43  552.67  590.41  693.71
River Rch & RM=481,53,7726.423
  391.35  468.16  558.49   597.4  703.11
River Rch & RM=481,53,7626.621
  394.76  472.84  564.23  604.32  712.42
River Rch & RM=481,53,7532.636
  425.88  515.81  617.06  668.37  799.35
River Rch & RM=481,53, 7438.65
  431.11  523.08  626.01  679.28  814.29
River Rch & RM=481,53,7250.679
  443.42  540.23  647.14  705.14  849.81
River Rch & RM=481,53,7186.077
  445.54  543.19  650.79  709.62  855.98
River Rch & RM=481,53,7098.431
   451.8  551.95  661.59  722.89   874.3
River Rch & RM=481,53,6922.164
  471.14  579.11  695.11  764.23  931.68
River Rch & RM=481,53,6779.522
  472.43  580.93  697.35  767.01  935.55
River Rch & RM=481,53,6657.762
  474.99  584.54  701.81  772.54  943.26
River Rch & RM=481,53,6527.358
  489.93  605.67  727.93  804.96  988.65
River Rch & RM=481,53,6395.328
  491.75  608.25  731.12  808.93  994.22
River Rch & RM=481,53,6192.842
  493.56  610.81  734.29  812.89  999.78
River Rch & RM=481,53,6101.767
  497.15   615.9  740.59  820.74 1010.82
River Rch & RM=481,53,5915.852
  504.21  625.94  753.01  836.25 1032.68
River Rch & RM=481,53,5729.936
  506.53  629.24   757.1  841.36  1039.9
River Rch & RM=481,53, 5544.02
  542.68  680.97  821.21  921.96 1154.52
River Rch & RM=481,53,5358.105
  553.43  696.46  840.44  946.29 1189.41
River Rch & RM=481,53,5150.626
  563.39  710.84   858.3  968.95 1222.01
River Rch & RM=481,53,4986.273
  579.25  733.82  886.86 1005.32 1274.57
River Rch & RM=481,53,4736.197
  582.06   737.9  891.94  1011.8 1283.97
River Rch & RM=481,53,4490.278
  591.29  751.33  908.65 1033.15 1314.98
River Rch & RM=481,53, 4295.59
  596.72  759.25   918.5 1045.77 1333.35
River Rch & RM=481,53,3875.785
  623.24  798.04  966.82 1107.88 1424.25
River Rch & RM=481,53,3552.956
  629.91  807.84  979.05 1123.66 1447.46
River Rch & RM=481,53,3364.652
  634.44   814.5  987.35 1134.39 1463.27
River Rch & RM=481,53,3171.443
  635.66   816.3   989.6  1137.3 1467.56
River Rch & RM=481,53,3006.795
  672.38  870.57 1057.35  1225.3 1598.05
River Rch & RM=481,53,2829.005
  674.62  873.89 1061.51 1230.73 1606.13
River Rch & RM=481,53,2651.214
   683.1   886.5 1077.27 1251.31 1636.88
River Rch & RM=481,53,2473.423
  821.34 1094.99 1338.79 1598.06 2164.84
River Rch & RM=481,53,2295.633
  834.13 1114.57 1363.42 1631.18 2216.21
River Rch & RM=481,53,2117.842
  838.15 1120.73 1371.18 1641.63 2232.43
River Rch & RM=481,53,1775.002
  842.14 1126.85 1378.88 1652.01 2248.58
River Rch & RM=481,53, 1417.28
  996.59 1366.73 1681.78 2065.73 2902.97
River Rch & RM=481,53,1122.583
  998.43 1369.62 1685.44 2070.79 2911.11
River Rch & RM=481,53,716.7172
  1002.3  1375.7 1693.15 2081.45 2928.24
River Rch & RM=481,53, 64.3668
  1022.1  1406.9 1732.66  2136.2 3016.43
Boundary for River Rch & Prof#=481,53,1
Up Type= 0
Dn Type= 2
Boundary for River Rch & Prof#=481,53,2
Up Type= 0
Dn Type= 2
Boundary for River Rch & Prof#=481,53,2
Up Type= 0
Dn Type= 2
Boundary for River Rch & Prof#=481,53,2
Up Type= 0
Dn Type= 2
Boundary for River Rch & Prof#=481,53,2
Up Type= 0
Dn Type= 2

--- 481_ras.g01 (geometry) ---

Geom Title=481
Program Version=4.10

River Reach=481,53
Reach XY= 30
1260228.29712793 619567.78327255 1259817.4639115619417.783329099
1259476.63067073619146.1167530421259354.13069493618736.116878375
1259169.13074479618573.6169320491258823.29749894618074.450423688
1258755.20473492617772.5458492931258829.32538188617687.706311509
1258804.13082194617528.6172529461258911.63078156617233.617337421
1259052.46406814617054.4507198181259419.96395329616837.784106791
1259465.79726923616704.4508117141259360.79728734616265.284278512
1259346.63061467 615916.11771594 1259402.1268813615767.303192556
1259282.33521464615710.0115258841259262.80396461615499.074025869
1259504.99146464615068.0844425561259520.79719669614780.284714833
1259623.29716024614567.7847749291259535.79717851 614309.45152086
1259597.46381882614030.2849352811259351.63054216613486.951770455
1259417.46385184613342.7851447021259503.29715931613326.951813579
1259811.63039219613001.9519010341259763.29706633612769.451971546
1259553.29712465612643.6186817141259627.46376437612471.118730754

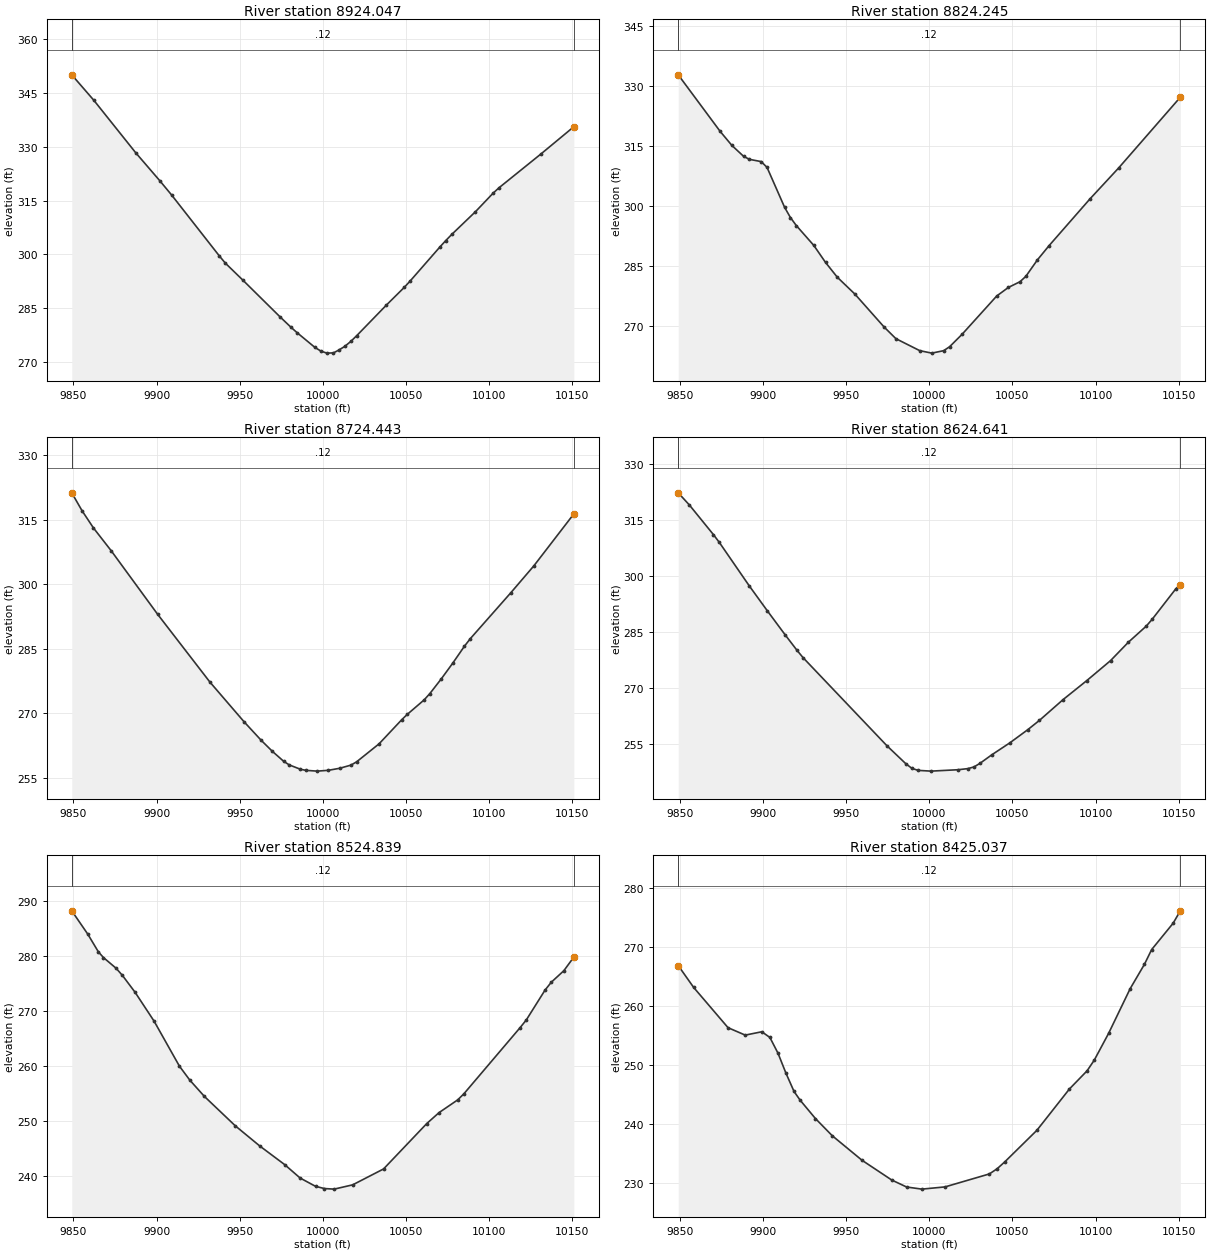
Type RM Length L Ch R = 1 ,8924.047,99.802000,99.802000,99.802000
XS GIS Cut Line= 5
1260288.96065317 619429.498546771260227.79818785 619566.45999677
1260226.97385216619568.282212641 1260217.6531438619589.173307194
1260167.57038219619706.015049037
#Sta/Elev= 30
9849.002350.05619862.312342.93659887.463328.32859901.836320.58879909.022316.5679
9937.767299.5553 9941.36 297.5569952.139292.70639974.229282.58989980.884279.6561
9984.477278.17869995.257274.0474 9998.85273.022110002.45272.4544 10006.4272.5254
10009.63273.309410013.22274.338910016.82275.709210020.41277.328310038.28285.8668
10048.99 290.78610052.56292.573910070.41302.042410073.97303.842110077.54 305.542
10091.82311.888110102.53317.1007 10106.1318.607810131.09327.9439   10151335.5843
#Mann= 3 , 0 , 0
9849.002    0.12       09849.002    0.12       0   10151    0.12       0
#XS Ineff= 2 , 0
       0                               0
Bank Sta=9849.002,10151
Exp/Cntr=0.3,0.1

Type RM Length L Ch R = 1 ,8824.245,99.802000,99.802000,99.802000
XS GIS Cut Line= 6
1260190.03195883619391.8725987511260143.98206975619510.354299377
1260134.68777097619531.251771329 1260133.8139631619533.050787672
1260122.78483174619558.4290600711260080.29109416619673.125726087
#Sta/Elev= 30
9849.013332.80679874.259318.64889881.299315.14859888.339312.42529891.859311.6722
9898.899311.11719902.419 309.6689912.979 299.6929916.499297.12179920.019295.1291
9930.578290.14439937.618285.89879944.658282.21779955.218  278.019972.817269.7656
9979.932 266.8449994.295263.843510001.51263.228810008.66263.842410012.24264.8319
10019.73267.932810040.59277.520810047.59279.654110054.58281.085610058.08282.4219
10065.08286.561410072.08290.115610096.57301.748910114.06309.593710150.99 327.205
#Mann= 3 , 0 , 0
9849.013    0.12       09849.013    0.12       010150.99    0.12       0
#XS Ineff= 2 , 0
       0                               0
Bank Sta=9849.013,10150.99
Exp/Cntr=0.3,0.1

Type RM Length L Ch R = 1 ,8724.443,99.802000,99.802000,99.802000
XS GIS Cut Line= 6
1260084.92510114619360.4011528711260055.69825108619439.906954512
1260046.06484065619473.3633900851260038.70982487619504.964917201
1260024.25014475619562.485950734 1259994.7044714619648.185781123
#Sta/Elev= 30
 9849.03321.2754  9855.2317.11589862.091313.09079872.677307.82869900.641293.0192
9932.101277.23079952.624267.99739962.968263.66489969.679261.10289976.418258.8039
9979.787257.95589986.525256.93869989.894256.68199996.633256.502310003.37256.6964
10010.14257.164710016.91257.902110020.29 258.65710033.82262.853410047.35268.4218
10050.74269.6953 10060.9273.070410064.37274.551710071.31278.011210078.25 281.694
10085.19285.586810088.66287.317710112.95297.969810126.84304.246310150.96316.3713
#Mann= 3 , 0 , 0
 9849.03    0.12       0 9849.03    0.12       010150.96    0.12       0
#XS Ineff= 2 , 0
       0                               0
Bank Sta=9849.03,10150.96
Exp/Cntr=0.3,0.1

Type RM Length L Ch R = 1 ,8624.641,99.802000,99.802000,99.802000
XS GIS Cut Line= 6
1260011.53086262619330.5103435541259962.71282708619439.631481446
1259948.07328851619466.3062955311259947.00766202619467.998761245
 1259934.0298164619492.4198589711259885.89562898619604.865082981
#Sta/Elev= 30
9849.029322.3398 9855.77319.05389870.147311.14689873.741309.02679891.712297.3793
9902.495 290.7329913.278284.23869920.466280.0472 9924.06278.10189974.618254.3881
9985.846249.62579989.588248.3459 9993.33247.8149   10001247.613910017.33247.9881
10023.18248.286110026.89248.738710030.53 249.71910037.67252.016510048.38255.1844
10059.08258.688310066.22261.228910080.49266.826510094.77271.936910109.04277.2944
10119.75282.231910130.46286.534110134.03288.3725 10148.3296.583310150.97297.6494
#Mann= 3 , 0 , 0
9849.029    0.12       09849.029    0.12       010150.97    0.12       0
#XS Ineff= 2 , 0
       0                               0
Bank Sta=9849.029,10150.97
Exp/Cntr=0.3,0.1

Type RM Length L Ch R = 1 ,8524.839,99.801900,99.801900,99.801900
XS GIS Cut Line= 6
1259927.80108242 619303.872985251259891.70767498619365.036612107
1259854.67572631619434.7775607691259853.64673485619436.492546652
1259814.64413899619510.1211733491259782.07932235619568.294333802
#Sta/Elev= 30
9849.018288.24379858.585284.03329865.041280.77649868.046279.75679875.665277.8059
9879.474276.50449887.093273.43529898.521268.18769913.759260.00649920.037257.4528
9928.774254.50239947.348249.15729962.206245.45729977.065   242.19986.362239.6603
9995.638238.1488   10001237.745410006.84237.641110017.98238.421910036.54241.3088
10062.53249.564410069.95251.561510081.09253.860210084.81 254.95810118.65266.9973
10122.41268.409110133.69273.841710137.45275.268910144.97277.353810150.99 279.836
#Mann= 3 , 0 , 0
9849.018    0.12       09849.018    0.12       010150.99    0.12       0
#XS Ineff= 2 , 0
       0                               0
Bank Sta=9849.018,10150.99
Exp/Cntr=0.3,0.1

Type RM Length L Ch R = 1 ,8425.037,99.802000,99.802000,99.802000
XS GIS Cut Line= 6
1259879.61759385619267.9850618841259851.13178549619302.666010751
1259828.56654829619327.1757581441259782.98314769619369.316402827
1259724.81582117619426.838683866 1259672.9710445619487.577955055
#Sta/Elev= 30
9849.026266.88259858.308263.16579878.984256.32519889.322255.06579899.298 255.635
9904.142254.66839908.986252.01329913.829248.57849918.673245.4871 9922.28244.0264
9931.533240.88749941.676 237.9589959.549233.79399977.421230.43729986.357229.2523
9995.544228.890410009.45229.267210036.11231.470110040.79232.350410045.46233.5393
10064.71238.888610084.31245.920810094.89248.997310099.21250.810410107.83255.3562
10120.78262.9454 10129.4267.106310133.72269.600310146.66 274.08810150.96276.1874
#Mann= 3 , 0 , 0
9849.026    0.12       09849.026    0.12       010150.96    0.12       0
#XS Ineff= 2 , 0
       0                               0
Bank Sta=9849.026,10150.96
Exp/Cntr=0.3,0.1

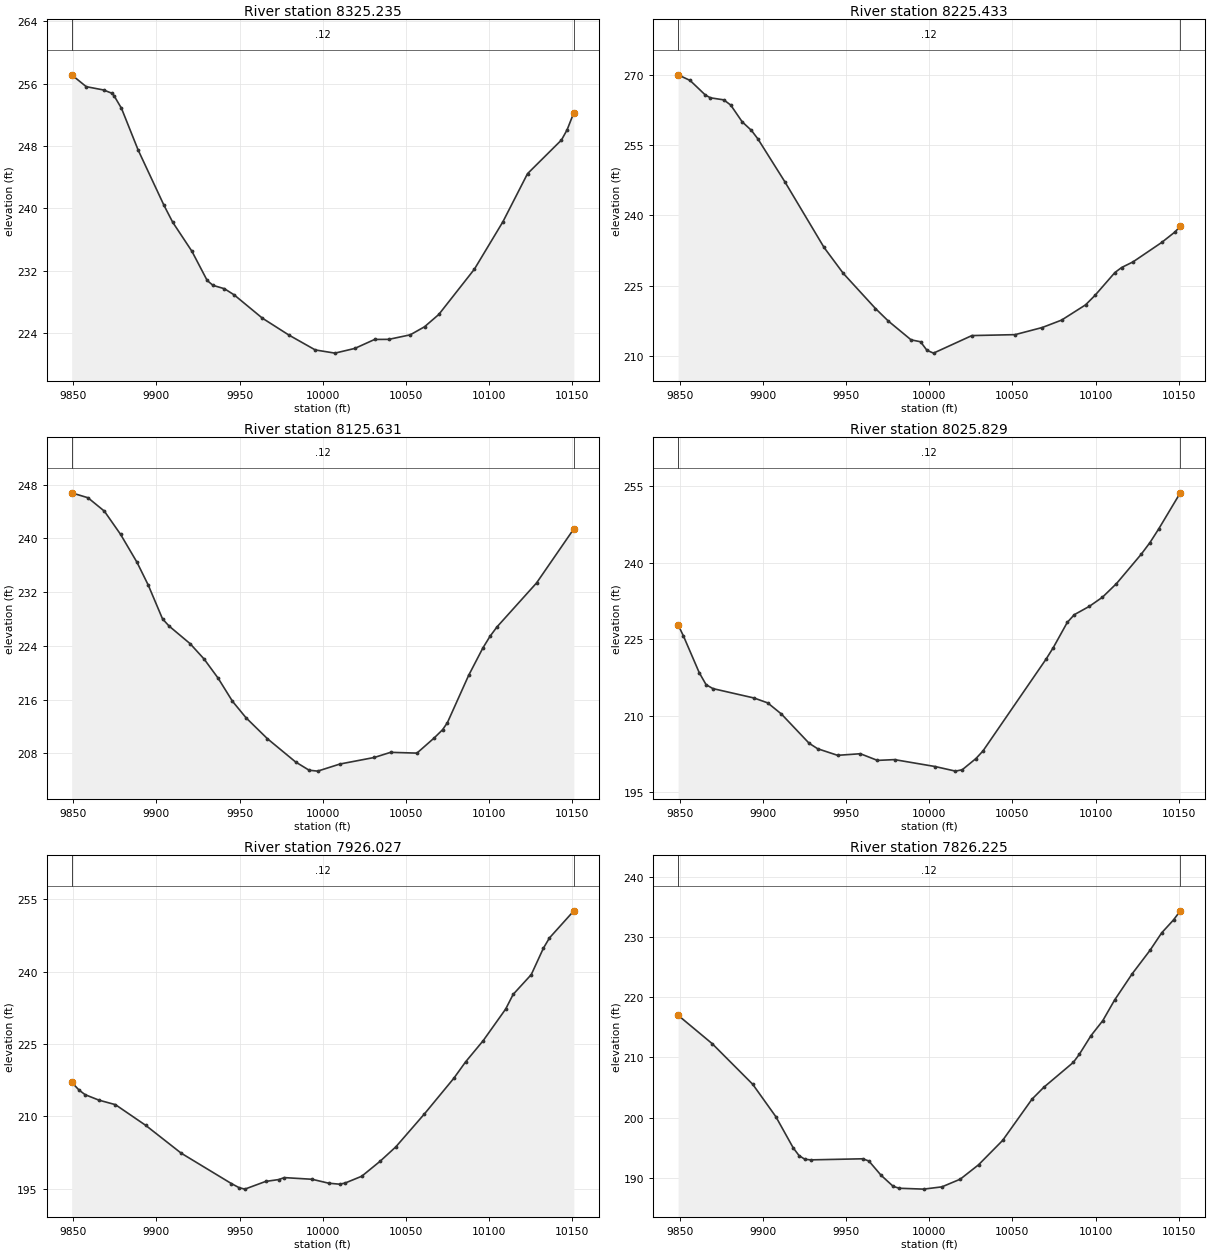
Type RM Length L Ch R = 1 ,8325.235,99.802000,99.802000,99.802000
XS GIS Cut Line= 6
1259807.14880596 619182.230482171259733.46967225619272.475944485
 1259714.7087457619300.1885162091259713.70447472619301.918094133
1259696.50485166619327.0035746611259619.58931904 619418.51973155
#Sta/Elev= 30
9849.032257.15229857.805255.63269868.263255.20549873.451 254.7689874.747 254.387
9878.982252.85749889.014247.49629904.577240.38499909.765238.23699921.336234.5023
9930.516230.74999934.043230.12329940.891 229.6929946.749228.9027 9963.69225.9149
9979.657223.74369995.505 221.83410007.33221.425310019.26 222.028 10031.2223.1818
10039.75223.194910052.61223.775910061.18224.807610069.75226.384810091.18232.2073
10108.32238.292610123.11244.462510143.51248.783810146.89250.081110150.96252.2917
#Mann= 3 , 0 , 0
9849.032    0.12       09849.032    0.12       010150.96    0.12       0
#XS Ineff= 2 , 0
       0                               0
Bank Sta=9849.032,10150.96
Exp/Cntr=0.3,0.1

Type RM Length L Ch R = 1 ,8225.433,99.802000,99.802000,99.802000
XS GIS Cut Line= 6
1259716.08395967619120.8893710851259674.05756273619178.113682844
1259632.26355137619245.1018082181259631.10107503619246.729275196
1259590.82296373619312.5925292721259548.93149361619372.082866128
#Sta/Elev= 30
9849.045270.12449856.243268.91929865.398265.80649868.454265.20189876.484264.7629
9880.666263.65089887.569260.05939893.111 258.2269896.948256.43439913.231247.2115
9936.773233.15879948.374227.5903 9967.71220.06999975.444217.38549989.096213.3664
9994.779212.95729998.646211.125310002.59210.521810025.66214.281610051.61214.4797
10067.96216.008710079.56217.590610093.99 220.85810099.62222.869110111.66227.7888
10115.67228.855310122.48230.054210139.75234.218710147.77236.477710150.96237.6992
#Mann= 3 , 0 , 0
9849.045    0.12       09849.045    0.12       010150.96    0.12       0
#XS Ineff= 2 , 0
       0                               0
Bank Sta=9849.045,10150.96
Exp/Cntr=0.3,0.1

Type RM Length L Ch R = 1 ,8125.631,99.802000,99.802000,99.802000
XS GIS Cut Line= 6
1259644.04411776619082.5273515491259614.08214288 619115.93937902
1259562.74611286619180.1798519431259545.94632265 619198.51328695
1259529.05833013619217.0804678741259449.29468578619313.173301966
#Sta/Elev= 30
 9849.02 246.7739858.813246.04219868.679244.0485 9878.47240.57899888.298236.4422
9895.062233.05219903.676228.00789907.662 226.9349920.261224.3227 9928.66222.0382
 9937.06219.20279945.719215.75469953.859213.3018 9966.74210.18179983.655206.7269
  9991.8205.49339996.958205.358410010.35206.415510030.95207.388510040.81208.1551
10056.64208.039610066.91210.272810072.05211.520910074.92212.554110087.71219.6006
10096.24 223.666 10100.5225.394110104.76226.816710128.55 233.35910150.98241.4138
#Mann= 3 , 0 , 0
 9849.02    0.12       0 9849.02    0.12       010150.98    0.12       0
#XS Ineff= 2 , 0
       0                               0
Bank Sta=9849.02,10150.98
Exp/Cntr=0.3,0.1

Type RM Length L Ch R = 1 ,8025.829,99.802000,99.802000,99.802000
XS GIS Cut Line= 6
1259588.57922331619042.7479335191259531.97552317619085.644920575
1259481.16742113 619127.858154041259468.99839338  619136.4711133
1259448.91426399619151.1579839311259351.82493466 619230.06339695
#Sta/Elev= 30
9849.012227.81429852.195225.6527 9861.72218.43859865.837216.08689869.953215.3186
9894.653213.47759902.886 212.5189911.119210.33469927.791204.59689932.925 203.523
 9944.92202.23129958.595202.54539968.862201.2377 9979.13201.3908 10003.6200.0306
10015.79199.132310019.85199.399910028.07201.5902 10032.3203.077410070.32221.1271
10074.57223.337710083.03228.311410087.26229.821510096.33231.464110104.17233.2424
10112.62235.919310127.54241.697610132.74243.963610137.99246.634410150.99253.7208
#Mann= 3 , 0 , 0
9849.012    0.12       09849.012    0.12       010150.99    0.12       0
#XS Ineff= 2 , 0
       09958.384                       0
Bank Sta=9849.012,10150.99
Exp/Cntr=0.3,0.1

Type RM Length L Ch R = 1 ,7926.027,99.802000,99.802000,99.802000
XS GIS Cut Line= 6
1259566.10922874618998.2173245651259478.00775259  619036.1914509
1259442.46489519619045.4748615181259400.95521757619051.495979487
1259366.40337633619061.7000401881259283.06363283619098.459923242
#Sta/Elev= 30
9849.061217.08119853.563215.44479857.198214.50059865.502 213.3699875.376212.4377
9893.553208.15469914.927202.37389945.091 196.0759949.787195.21299953.177194.9231
 9965.66196.51729973.523196.90649976.914197.31219993.587196.966210003.52196.1562
10010.16195.944410013.48196.189710023.44197.596610034.43200.687410043.96203.6984
 10061.1210.509710078.78217.903210085.85221.299310096.46225.715610109.97232.2705
10114.44235.294610125.35239.405310132.63244.870510136.26246.999510150.94252.6281
#Mann= 3 , 0 , 0
9849.061    0.12       09849.061    0.12       010150.94    0.12       0
#XS Ineff= 2 , 0
       09970.949                       0
Bank Sta=9849.061,10150.94
Exp/Cntr=0.3,0.1

Type RM Length L Ch R = 1 ,7826.225,99.802000,99.802000,99.802000
XS GIS Cut Line= 6
1259541.96421406618897.7325684241259438.81469524 618934.35585713
1259402.44760626618952.1852022251259400.66847225618953.098811648
1259367.73977077618969.5916004941259262.98512993619012.360147669
#Sta/Elev= 30
9849.039216.97949869.506212.28379893.877205.54629907.803200.16539918.247194.9912
9921.729 193.721 9925.21193.10459928.692193.00079960.101193.18119963.755 192.809
9971.062190.4471 9978.37188.60499982.024188.2927 9996.64188.148110007.65188.5243
10018.66 189.79710029.65192.178310044.12196.218710061.84203.081210068.92 205.044
10086.64209.169910090.19210.480710097.27213.601910104.36216.091410111.45 219.503
10122.08223.879810132.71227.7396 10139.8230.663210146.89232.798110150.98  234.31
#Mann= 3 , 0 , 0
9849.039    0.12       09849.039    0.12       010150.98    0.12       0
#XS Ineff= 2 , 0
       09965.547                       0
Bank Sta=9849.039,10150.98
Exp/Cntr=0.3,0.1

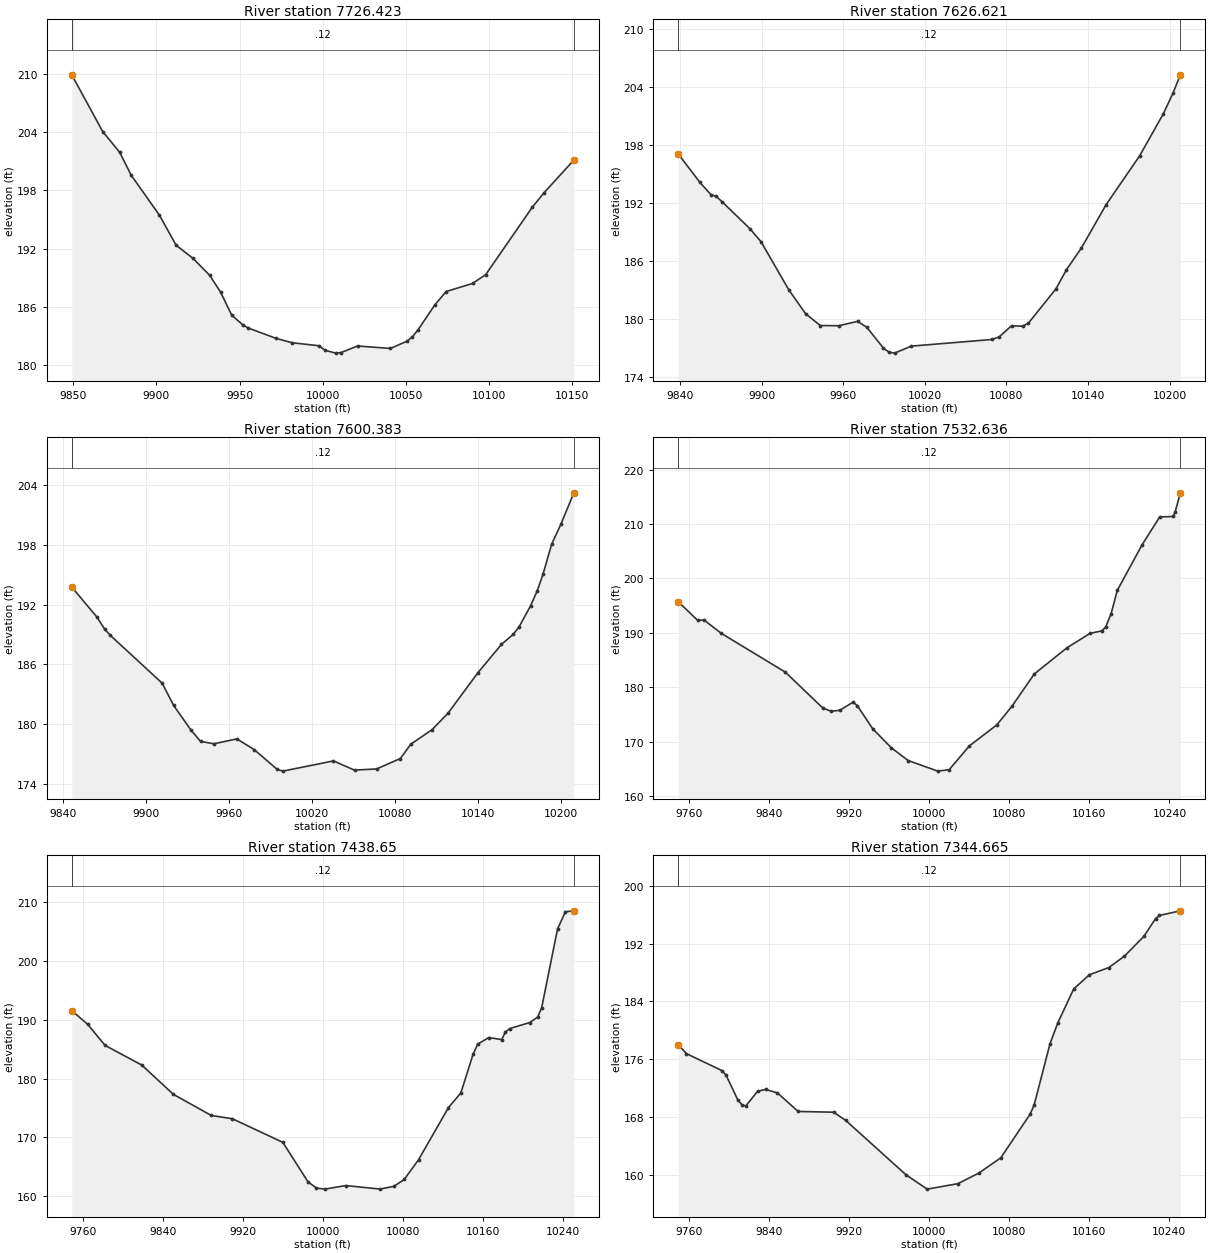
Type RM Length L Ch R = 1 ,7726.423,99.802100,99.802100,99.802100
XS GIS Cut Line= 6
1259524.16165778618833.9675389561259426.04075047618857.605086911
1259350.08968303618858.6853725811259316.20997942618862.871619321
1259272.64970288618874.8644322741259230.36910726618891.514394518
#Sta/Elev= 30
9849.061209.92099867.659204.06959877.891201.92269884.713 199.5819901.766195.4348
9911.826192.33289921.847190.99929931.867189.25729938.547187.49599945.228185.1255
9951.881184.12169955.171183.79919971.621 182.7449981.489182.27819997.903181.9624
 10001.2181.501510007.76181.205810011.04181.269610020.88181.941610040.68181.6898
10050.59182.4342 10053.9182.894810057.21183.605110067.32186.178910074.13187.5638
 10090.1188.395810097.95189.314710125.89196.249310132.94 197.74610150.91201.1218
#Mann= 3 , 0 , 0
9849.061    0.12       09849.061    0.12       010150.91    0.12       0
#XS Ineff= 2 , 0
       09961.445        10063.85       0
Bank Sta=9849.061,10150.91
Exp/Cntr=0.3,0.1

Type RM Length L Ch R = 1 ,7626.621,26.237900,26.237900,26.237900
XS GIS Cut Line= 2
1259495.97850442618663.9794596581259200.14517111618884.812792987
#Sta/Elev= 30
9838.681197.06029854.493194.13229862.682192.85049866.776192.6554 9870.87 192.118
9891.341189.33389899.529187.98489919.999     1839932.282180.54649943.078179.3122
9956.846179.29279970.501179.74269977.317179.13569989.599176.97079993.694176.5557
9997.788176.458410010.07177.182710069.22177.867810074.71178.140210083.76179.2915
10091.95179.238110096.05179.538310116.52183.128210124.07185.069410135.04 187.314
10153.36191.825810177.93196.853810195.37201.212710202.49203.344310207.85205.2364
#Mann= 3 , 0 , 0
9838.681    0.12       09838.681    0.12       010207.85    0.12       0
#XS Ineff= 2 , 0
       09973.606        10047.37       0
Bank Sta=9838.681,10207.85
Exp/Cntr=0.3,0.1

Type RM Length L Ch R = 1 ,7600.383,67.747500,67.747500,67.747500
XS GIS Cut Line= 3
1259475.83961558 618643.146126331259332.16160357618754.629581422
1259193.96715909618871.296248108
#Sta/Elev= 30
9846.634193.75019864.749190.75629870.403189.53839874.556188.9036 9911.93184.1275
9920.235181.89189932.693179.43949939.675178.29539949.303178.05449965.914178.5457
9978.372177.47699994.982175.49599999.135 175.31610035.63176.338510050.89175.4158
10066.84175.534810084.01176.577210091.58178.018610106.84179.458310118.36181.1024
10139.83185.1335   10157188.001610165.59189.018210169.88189.791610178.04191.8567
10182.76193.331910187.06195.0199 10193.3 198.03810199.94200.025710209.35203.1877
#Mann= 3 , 0 , 0
9846.634    0.12       09846.634    0.12       010209.35    0.12       0
#XS Ineff= 2 , 0
       09969.152        10041.56       0
Bank Sta=9846.634,10209.35
Exp/Cntr=0.3,0.1

Type RM Length L Ch R = 1 ,7532.636,93.985400,93.985400,93.985400
XS GIS Cut Line= 6
 1259486.1707293618541.1646809641259332.78309447618655.442646023
1259306.30937222618684.7656467991259279.69280579618732.001182575
1259247.68748398618764.1958131291259104.93136283618858.127170895
#Sta/Elev= 30
9749.092195.71439768.514192.27669774.914192.33949792.249189.87899856.197182.7547
9893.571176.16799901.976175.56779910.668175.75419923.746177.23779928.053176.6144
9943.519172.34499962.048168.85729978.869166.520210008.49164.567110019.86164.8349
10040.16169.215410067.41 173.04910082.65176.492210104.95182.424310137.47187.2183
10160.77189.897310172.36190.338710176.23191.016510181.72193.481910187.93197.7959
10212.77206.190110230.32 211.29410243.83211.373910245.78212.205610250.91215.7211
#Mann= 3 , 0 , 0
9749.092    0.12       09749.092    0.12       010250.91    0.12       0
#XS Ineff= 2 , 0
       09929.085        10041.42       0
Bank Sta=9749.092,10250.91
Exp/Cntr=0.3,0.1

Type RM Length L Ch R = 1 , 7438.65,93.985500,93.985500,93.985500
XS GIS Cut Line= 6
1259452.57130163618474.830572614  1259351.324691618545.906431119
1259237.65653839618636.6481666511259152.70291309618707.673563504
1259101.72038882618745.3666318761259053.11222601618778.198178057
#Sta/Elev= 30
9749.016191.58189764.742189.28299782.296185.66929818.998182.31939850.619177.3298
9888.592173.73419909.607173.18169960.042169.1637 9985.26162.42719993.666161.3883
10002.04161.2017   10023161.806510057.21161.213210071.21161.683910081.44162.8559
 10095.7166.201510125.63175.082610138.02177.577210150.27 184.17110154.95185.8981
10165.99187.005810178.83186.646310182.54187.936310186.99188.538310206.94189.5558
10214.86190.490110218.82192.075310234.65205.470710242.57208.405710250.98208.5689
#Mann= 3 , 0 , 0
9749.016    0.12       09749.016    0.12       010250.98    0.12       0
#XS Ineff= 2 , 0
       09944.244        10113.51       0
Bank Sta=9749.016,10250.98
Exp/Cntr=0.3,0.1

Type RM Length L Ch R = 1 ,7344.665,93.985400,93.985400,93.985400
XS GIS Cut Line= 6
1259378.57155402618432.9569521631259287.04579579618494.519809896
1259185.88294755618566.3420984731259159.21356778618590.625909953
1259117.66087676618621.233848287 1258967.0034444618719.421092149
#Sta/Elev= 30
9749.048178.01449757.259176.77929792.845174.42849796.799173.8184 9808.66170.3666
9812.614169.73659816.568169.5366 9828.43171.58159836.338171.8271  9848.2171.3534
9868.908 168.7849904.334168.68089916.405 167.5549976.759160.02179997.924158.0424
10028.54158.794610049.34160.244410071.49162.373710100.95168.4348 10104.9169.7068
 10120.7 178.151 10128.6181.0634 10144.4185.727710160.06187.686310179.51188.6873
10195.07190.257410214.52192.990210226.18195.455510230.07195.889410250.96196.5288
#Mann= 3 , 0 , 0
9749.048    0.12       09749.048    0.12       010250.96    0.12       0
#XS Ineff= 2 , 0
       09910.964        10046.86       0
Bank Sta=9749.048,10250.96
Exp/Cntr=0.3,0.1

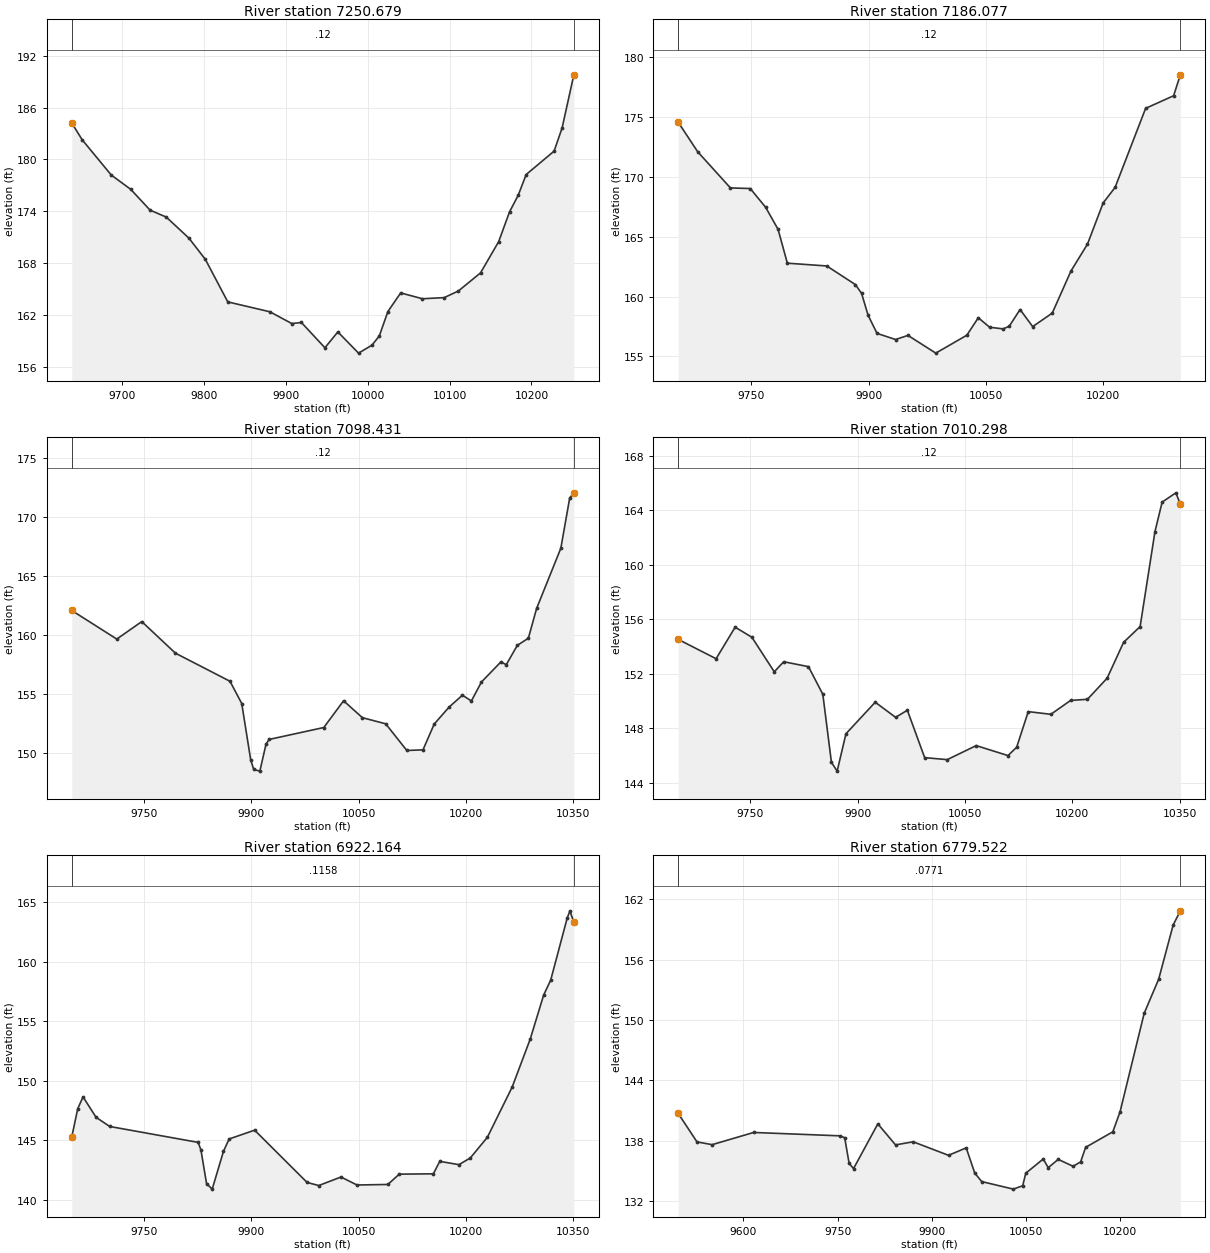
Type RM Length L Ch R = 1 ,7250.679,64.602400,64.602400,64.602400
XS GIS Cut Line= 4
1259444.58961552618284.1183485241259161.25628218618475.090570748
1259130.70072666618507.7294596581258962.57190967 618660.65191336
#Sta/Elev= 30
9638.212184.22489650.869182.27819686.477178.19259710.216176.54399733.955174.1289
9753.738 173.3249781.433170.88819801.496168.43049828.911163.51359880.346162.3715
9907.156161.00699918.896161.13079947.606158.20729963.432160.03939988.723157.5855
 10005.1158.504410014.09159.569610024.61162.401910040.24164.551610066.83163.8775
10093.46164.009410110.71164.772610137.81166.868610159.98170.481710173.29173.9342
10183.85175.844510193.61178.251110227.74180.958310237.49 183.62810251.88189.7877
#Mann= 3 , 0 , 0
9638.212    0.12       09638.212    0.12       010251.88    0.12       0
#XS Ineff= 2 , 0
       09957.508           10034       0
Bank Sta=9638.212,10251.88
Exp/Cntr=0.3,0.1

Type RM Length L Ch R = 1 ,7186.077,87.645700,87.645700,87.645700
XS GIS Cut Line= 4
1259408.78232387  618239.63050131259125.44899055618430.602723539
1259090.61010408618454.4887188971258895.29760411618623.759552225
#Sta/Elev= 30
9656.443174.56489681.309172.09939723.224169.07559748.569169.02519768.352167.4504
9784.178165.61189796.047162.78669846.494 162.5539883.091160.99739891.004160.2662
9899.324158.43889910.786156.91829934.525156.40649950.351156.7516 9985.96 155.269
10025.67156.765110040.37158.225910054.83 157.43210072.09157.295710079.88157.5098
10093.79158.912910109.94157.485510134.98158.614710158.92162.131410180.07164.3822
10200.11167.821910215.36169.117310254.43175.724910290.28176.780810298.82178.5274
#Mann= 3 , 0 , 0
9656.443    0.12       09656.443    0.12       010298.82    0.12       0
#XS Ineff= 2 , 0
       09960.273        10040.35       0
Bank Sta=9656.443,10298.82
Exp/Cntr=0.3,0.1

Type RM Length L Ch R = 1 ,7098.431,88.133700,88.133700,88.133700
XS GIS Cut Line= 6
1259353.75882273618155.0658127751259245.43886914618221.260053705
1259148.56939049618290.2949177451259053.16246606618391.119509592
1259018.22545583618420.1350326591258789.40994229  618565.3606583
#Sta/Elev= 30
9649.045162.09679711.972159.67389746.896161.15699793.915158.48069870.254 156.098
9886.664154.21199899.142149.45129903.419148.62239911.973148.48319920.527 150.752
9924.805151.166510001.35152.179510029.03154.444810055.31153.012510087.89152.4941
10117.43150.2322   10140150.285610155.78152.477710176.52153.910910195.15154.9186
10207.66154.427910221.82156.0397 10248.8157.7301 10256.5157.509210271.92159.1431
10287.33159.747210298.89162.272910332.74167.373410345.14171.638710350.92172.0688
#Mann= 3 , 0 , 0
9649.045    0.12       09649.045    0.12       010350.92    0.12       0
#XS Ineff= 2 , 0
       09944.308        10054.04       0
Bank Sta=9649.045,10350.92
Exp/Cntr=0.3,0.1

Type RM Length L Ch R = 1 ,7010.298,88.133800,88.133800,88.133800
XS GIS Cut Line= 6
1259309.28151185618101.5501116031259242.38685612618140.381133151
1259185.45228094618177.191527044 1258900.0175329618382.107850032
1258816.28929753618437.3948698991258726.76562926618492.318955882
#Sta/Elev= 30
9649.028154.52879701.974153.10939728.593155.42629752.034154.68449783.288152.1481
9796.502152.88789831.127152.5262 9851.18150.49589863.212145.49599871.233144.8538
9883.507 147.599 9924.46149.91449952.924148.80519969.369149.32479993.572145.8427
10025.16145.6988 10065.6146.728410110.08145.996310122.21 146.61110138.38149.2235
10170.04149.027310197.56150.045610221.15150.129710248.61151.675210271.71154.3144
 10294.8155.474510315.57162.450510325.59164.614510344.84165.292710350.98164.4524
#Mann= 3 , 0 , 0
9649.028    0.12       09649.028    0.12       010350.98    0.12       0
#XS Ineff= 2 , 0
       0 9927.66        10061.24       0
Bank Sta=9649.028,10350.98
Exp/Cntr=0.3,0.1

Type RM Length L Ch R = 1 ,6922.164,142.641900,142.641900,142.641900
XS GIS Cut Line= 6
1259274.16616386618041.298743198 1259163.7352618618103.749262268
 1259018.6279525618200.6882253121258922.33085065618250.843600515
1258780.03364561618348.1326416131258678.13413934618410.497732753
#Sta/Elev= 30
9649.044145.2784  9657.4147.65959664.815148.64349683.058146.92769702.122146.1612
9825.644144.8258 9829.59 144.2049837.481141.36199845.372140.90079861.155144.0779
9869.046145.11179904.666145.85129978.046141.46069994.343141.203210025.43141.9184
10047.78141.247810090.96141.292710106.85142.157510154.55 142.187 10163.5143.2326
10190.32142.955510206.21143.516810230.06145.254410264.72149.470710289.96153.4981
10308.82157.208410318.58158.447410341.65163.6619 10345.5164.269210350.95163.2912
#Mann= 3 , 0 , 0
9649.044  0.1158       09649.044  0.1158       010350.95  0.1158       0
#XS Ineff= 2 , 0
       09926.957        10106.32       0
Bank Sta=9649.044,10350.95
Exp/Cntr=0.3,0.1

Type RM Length L Ch R = 1 ,6779.522,121.759400,121.759400,121.759400
XS GIS Cut Line= 5
1259346.68649301617934.7404550461258895.94029424618110.411802217
1258874.58779514618122.8054060641258732.29059008618220.094447181
1258630.39108381618282.459538311
#Sta/Elev= 30
9496.016140.69329525.897137.86939550.094137.59399616.245138.80679754.324138.4696
9761.366138.27679768.409135.73349775.451135.21549814.184139.66239842.354137.5715
9870.523137.87869926.862136.53289955.032137.27539968.605134.7763 9979.68133.9237
10030.16133.171210045.08133.510910050.03134.755710077.85136.167910085.77135.3054
10101.69136.128510125.54135.441110137.46135.885210145.41137.328810188.74138.8706
10200.27140.858810238.74150.659410261.82 154.046 10284.9159.433310296.32 160.847
#Mann= 3 , 0 , 0
9496.016  0.0771       09496.016  0.0771       010296.32  0.0771       0
#XS Ineff= 2 , 0
       09950.584        10110.98       0
Bank Sta=9496.016,10296.32
Exp/Cntr=0.3,0.1

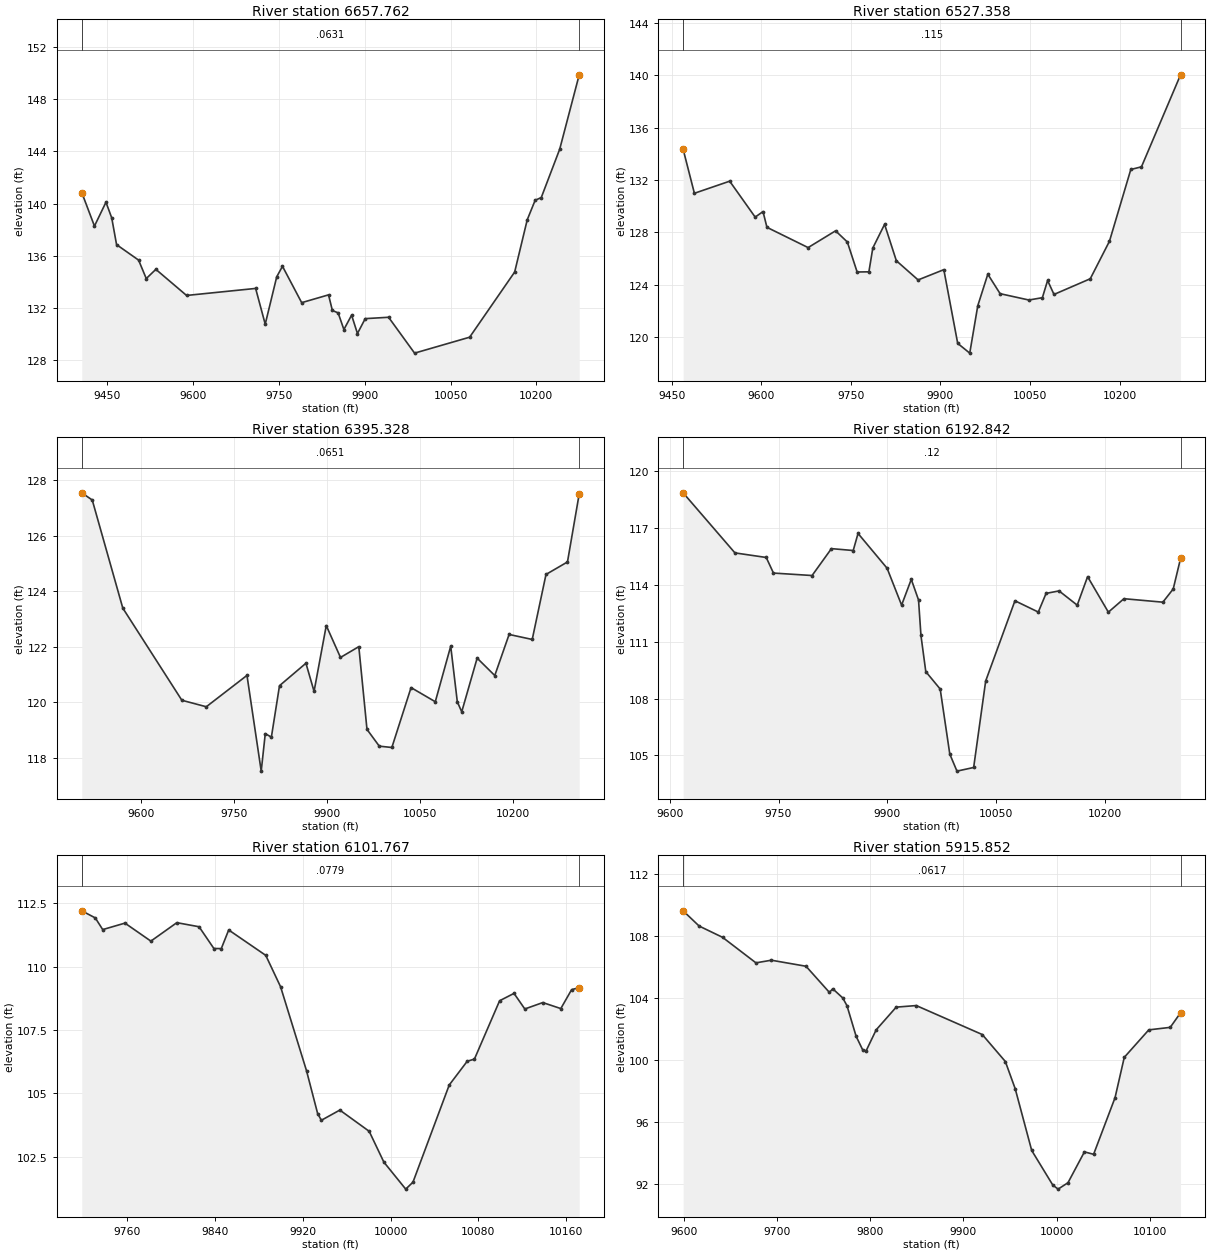
Type RM Length L Ch R = 1 ,6657.762,130.404100,130.404100,130.404100
XS GIS Cut Line= 6
1259383.57885411617893.5078161211258926.76461798617991.164066136
1258847.36739329  618013.06800131258821.32572663618023.484667972
1258786.16947666618037.807584658   1258553.09656618139.370084643
#Sta/Elev= 30
 9405.25140.84319427.403138.27659447.532140.10539457.597138.90539466.064 136.856
9504.567 135.6719517.987134.25649534.761134.96319588.441132.9639 9709.22133.5017
9725.994130.76339746.124134.39439756.189 135.1979789.739132.41159836.708133.0092
9843.418131.81169853.483131.62939863.548130.35389877.034131.45599887.244130.0481
9900.858131.18849941.698131.29279987.147128.546810083.43129.766510162.16134.7587
10184.13138.759410197.95140.251210208.69140.4643 10240.9144.1659   10275149.8609
#Mann= 3 , 0 , 0
 9405.25  0.0631       0 9405.25  0.0631       0   10275  0.0631       0
#XS Ineff= 2 , 0
       09953.679        10050.75       0
Bank Sta=9405.25,10275
Exp/Cntr=0.3,0.1

Type RM Length L Ch R = 1 ,6527.358,132.030700,132.030700,132.030700
XS GIS Cut Line= 6
1259324.98510408 617859.870663361258968.97730172617870.039561912
1258870.18455854617883.5339802351258815.44703743617895.636262208
1258731.69309753617921.9749177991258517.69343743618013.950524464
#Sta/Elev= 30
9469.272134.35129488.123130.98639547.202131.91049589.871129.16599602.999129.5894
9609.564128.38619678.489126.8381 9724.44128.11849744.133127.26739760.543124.9743
9780.236124.98669786.801126.80789806.494128.61379826.194125.83359862.618124.3676
9905.665125.15239928.898119.52139949.059 118.7769962.499122.39659979.299124.8037
9999.875123.317510048.03122.833110070.64 123.01110079.38124.325410090.09123.2587
 10150.8124.456710182.94127.323810218.65132.8039 10236.5133.007410301.92140.0348
#Mann= 3 , 0 , 0
9469.272   0.115       09469.272   0.115       010301.92   0.115       0
#XS Ineff= 2 , 0
       09986.292        10080.86       0
Bank Sta=9469.272,10301.92
Exp/Cntr=0.3,0.1

Type RM Length L Ch R = 1 ,6395.328,202.485500,202.485500,202.485500
XS GIS Cut Line= 6
 1259250.8242245 617779.032989741259029.20101172617765.402935952
1258810.53389588617767.7473150191258773.99032721617771.551371455
1258733.45039329617781.4292837081258471.74436334617890.795142516
#Sta/Elev= 30
9504.375 127.5389521.268127.27889570.573123.38399665.897 120.0649705.342119.8301
9771.001120.96029793.968117.5109 9800.53118.86159810.373118.73539823.497120.5892
 9866.15121.39789879.274120.38439898.961 122.7559921.928121.60649951.491121.9954
9964.685119.01489984.535118.410310004.83118.362610035.82120.520710074.94120.0108
10099.82 122.01210110.49120.0071 10117.6119.648210142.49121.582110170.94120.9552
10194.06122.435210231.39122.254910253.62124.597510288.28125.047410307.21127.4992
#Mann= 3 , 0 , 0
9504.375  0.0651       09504.375  0.0651       010307.21  0.0651       0
#XS Ineff= 2 , 0
       09957.476        10055.53       0
Bank Sta=9504.375,10307.21
Exp/Cntr=0.3,0.1

Type RM Length L Ch R = 1 ,6192.842,91.074800,91.074800,91.074800
XS GIS Cut Line= 6
1259199.56474009617674.0142227561259049.07304463617651.700827494
1258869.33157423617619.6177058071258802.38735586617613.612059727
1258754.94748834 617620.612850861258539.01866895617713.928823084
#Sta/Elev= 30
9618.572118.84959689.932115.68199733.049115.44039742.999114.61769796.188114.4888
 9822.85115.90699852.844115.80719859.509116.70749899.502114.87419919.498112.9274
9932.829114.28639942.827113.20039946.159111.32629952.825109.42039972.659 108.501
 9985.88105.07199995.765104.172910018.76104.365310035.32108.926910075.63113.1569
 10107.8112.561510118.52113.546410136.39113.677110161.41112.926210175.71114.4287
 10204.3112.555710225.75113.266210279.36113.082810293.65113.780110303.73115.3877
#Mann= 3 , 0 , 0
9618.572    0.12       09618.572    0.12       010303.73    0.12       0
#XS Ineff= 2 , 0
       09965.862        10106.35       0
Bank Sta=9618.572,10303.73
Exp/Cntr=0.3,0.1

Type RM Length L Ch R = 1 ,6101.767,185.915600,185.915600,185.915600
XS GIS Cut Line= 6
1259078.60532725 617591.115845741258853.81233895617535.978531197
1258805.71040177617526.4983333651258803.77384716617525.998577401
1258756.46658564617519.9184063971258633.20269671617521.654517516
#Sta/Elev= 30
9718.516 112.2029730.835111.92229737.592111.4617 9757.86111.71719781.507111.0068
9805.153111.73489825.422111.57399838.934110.7157 9845.69110.71179852.446111.4468
9886.227110.4453 9899.74 109.2069923.386105.8923 9933.52104.20479936.898 103.938
 9953.75 104.3419980.502103.50459993.878102.289310013.83101.222310020.44101.4978
10053.48105.330310069.89106.267710076.45 106.35210099.42108.654610112.54 108.945
10122.39108.329810138.79108.5825 10155.2108.345810165.04109.091110171.97109.1732
#Mann= 3 , 0 , 0
9718.516  0.0779       09718.516  0.0779       010171.97  0.0779       0
#XS Ineff= 2 , 0
       09939.593        10092.37       0
Bank Sta=9718.516,10171.97
Exp/Cntr=0.3,0.1

Type RM Length L Ch R = 1 ,5915.852,185.915700,185.915700,185.915700
XS GIS Cut Line= 6
1259236.57532075617511.4537461251258998.67577851617406.350339636
1258868.97806799617353.9057493211258867.14194331617353.112877324
1258841.53964618 617342.595529691258737.36936337617334.154517502
#Sta/Elev= 30
9599.018109.6004 9616.22 108.6219641.327107.89749677.195 106.2549693.799106.4232
9730.996106.03429756.103 104.352 9759.69104.58549770.451103.99519774.985103.4957
9784.798101.52969791.971100.63899795.558 100.5969806.318101.94249827.839103.4046
9849.359103.50599920.267101.64159945.03999.906819955.65698.149249973.351 94.1837
9995.97191.9601310001.6891.6960810012.3292.1082810029.96 94.092210039.8393.93688
10062.8797.5824310072.75100.173810099.08101.941610122.12102.103310133.19103.0385
#Mann= 3 , 0 , 0
9599.018  0.0617       09599.018  0.0617       010133.19  0.0617       0
#XS Ineff= 2 , 0
       09875.921        10120.36       0
Bank Sta=9599.018,10133.19
Exp/Cntr=0.3,0.1