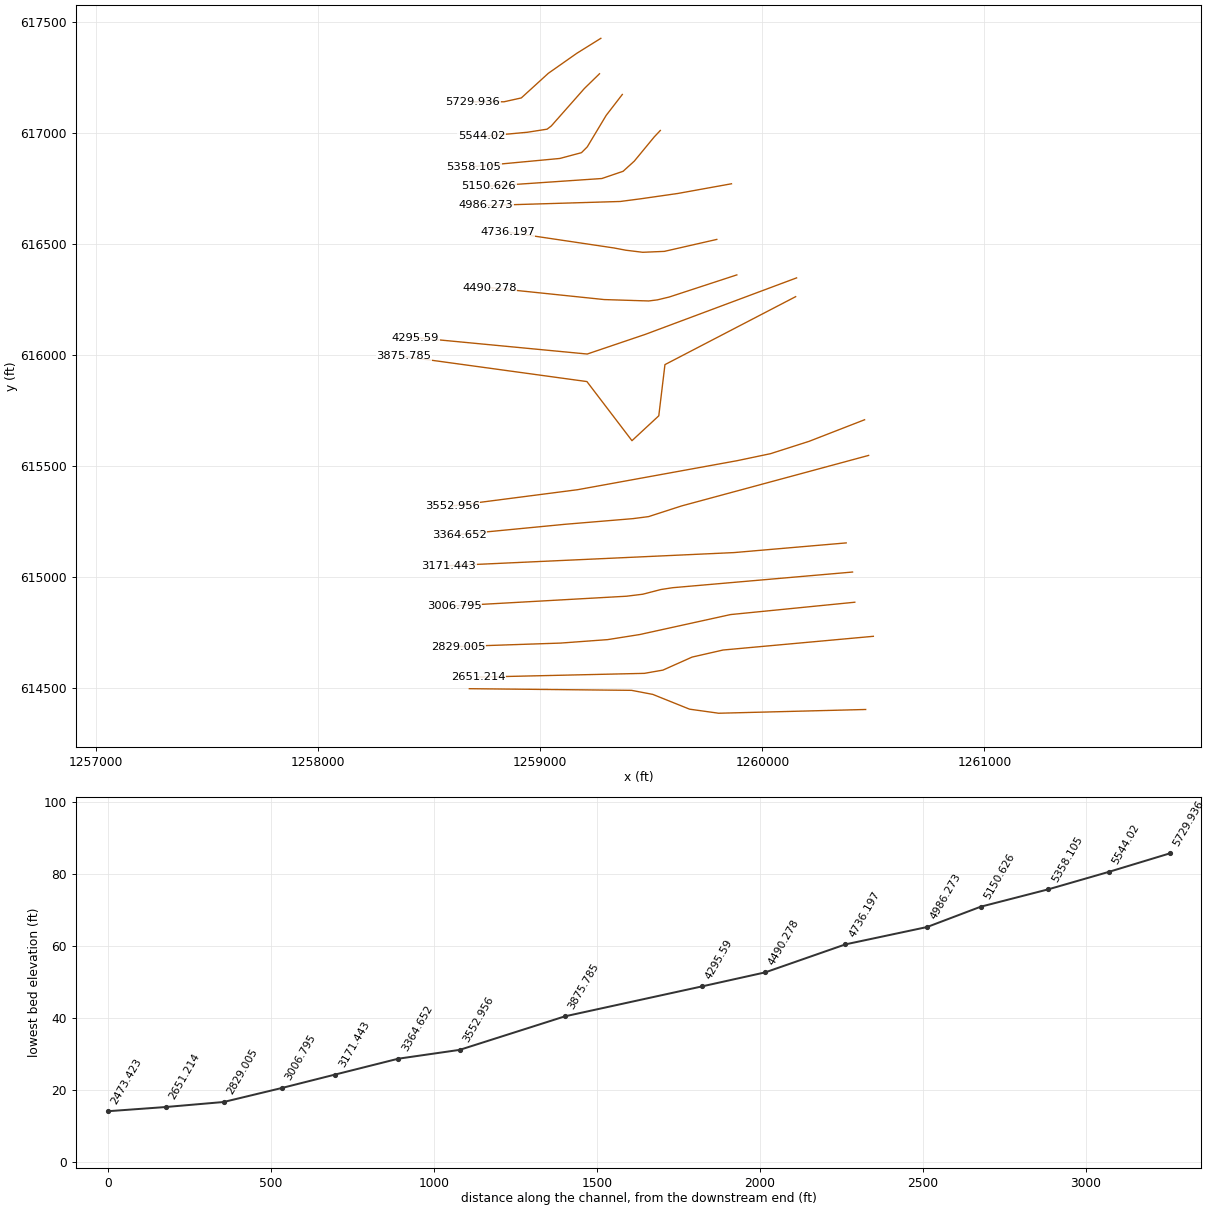
HEC-RAS study 481_ras.prj: 481

--- 481_ras.g01 (geometry) --- (continued)

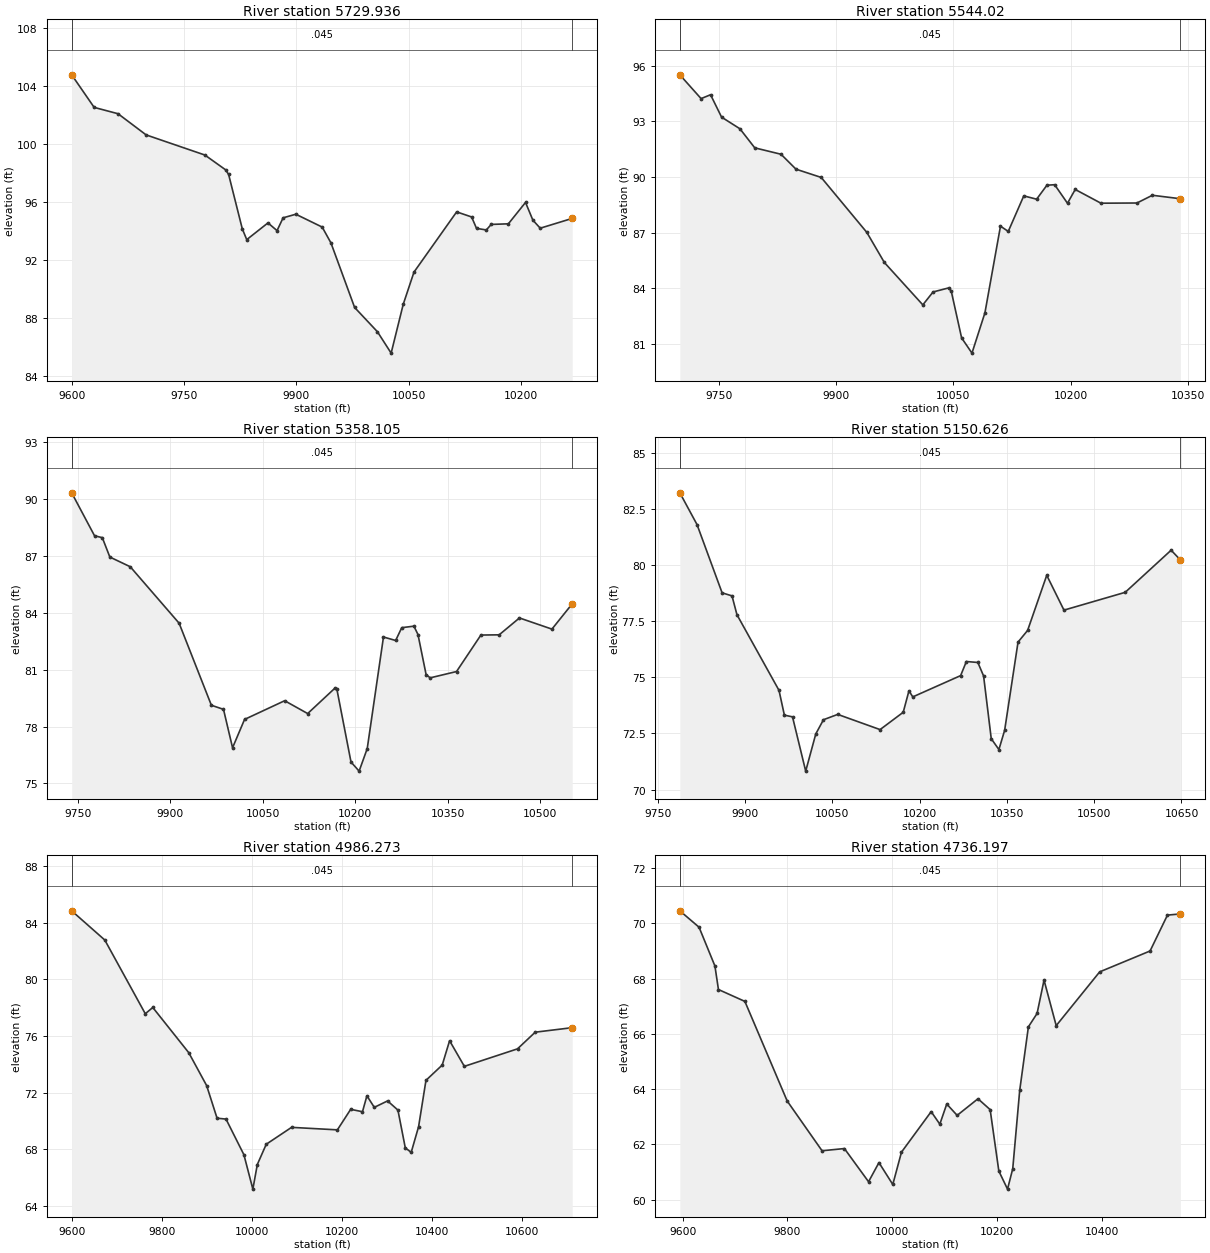
Type RM Length L Ch R = 1 ,5729.936,185.915700,185.915700,185.915700
XS GIS Cut Line= 6
 1259272.6216962 617427.195863471259164.52754942 617359.88268365
1259036.06162474617269.6451515561258914.45269671617158.807295293
1258836.32769671617141.4461841731258695.70269671617141.446184173
#Sta/Elev= 30
9599.069104.7626 9629.15102.52039661.089 102.0859698.719100.62719777.39599.24079
  9805.298.220059809.17297.903049827.47894.158819833.43593.416779861.83394.56839
9874.00394.036779882.11694.918299899.144 95.16579934.45794.280329946.16193.19259
9977.85788.74738 10008.4 87.075510026.7685.6034710042.9488.9631910057.3491.18166
10114.47 95.327610134.4994.9777310141.0694.1915710154.18 94.083610160.7494.46417
10183.7194.5058310206.6795.9787610216.5294.7578810226.3694.2042210269.2194.87842
#Mann= 3 , 0 , 0
9599.069   0.045       09599.069   0.045       010269.21   0.045       0
#XS Ineff= 2 , 0
       09916.632         10092.3       0
Bank Sta=9599.069,10269.21
Exp/Cntr=0.3,0.1

Type RM Length L Ch R = 1 , 5544.02,185.915600,185.915600,185.915600
XS GIS Cut Line= 6
1259266.56923932617267.6686762571259198.63784739617201.471464008
1259049.63807258617032.7605150491259030.77214113617018.182295293
1258942.23047447617004.2934064121258735.63325223616985.196184173
#Sta/Elev= 30
9699.52895.514469726.73194.23128 9738.8794.440659752.97393.232629776.47892.60464
9795.49791.575179829.10691.230259848.31190.42463 9880.6289.979069939.03787.01548
9961.50585.3913110010.7883.10499 10023.983.8012210043.8484.0193310047.1683.85439
10060.45 81.325310073.7380.5018310090.3482.6757810110.2687.3500610120.2387.06738
 10140.188.9842910156.5788.8058610169.7589.5596510179.6489.5870710196.1188.58595
10205.9989.3302510238.9488.5896110285.0788.6001410304.84 89.017410340.7288.83007
#Mann= 3 , 0 , 0
9699.528   0.045       09699.528   0.045       010340.72   0.045       0
#XS Ineff= 2 , 0
       0                10061.53       0
Bank Sta=9699.528,10340.72
Exp/Cntr=0.3,0.1

Type RM Length L Ch R = 1 ,5358.105,207.479200,207.479200,207.479200
XS GIS Cut Line= 6
1259369.31380779617174.4322952931259296.46775502617079.981605962
1259211.62677485 616938.620262341259185.28603002616912.279517516
1259088.06380779616886.2378508451258699.17491895616849.779517516
#Sta/Elev= 30
9739.82390.342619776.90788.075689789.54187.975899801.76786.952639834.91386.43986
9914.25383.458939966.61879.128199986.29778.91145   1000176.8835810020.4978.38039
 10085.679.3671510122.9678.6896610166.9680.0233410170.2579.9975410193.3276.13093
 10206.575.6504410219.6876.8427510246.0482.7310610265.8182.54695 10275.783.22399
10295.4783.3032710302.0682.8617810315.2480.7482510321.8380.5745610364.6780.90855
10404.2182.8342710433.87 82.845910466.8283.7370310519.5483.1476310552.51 84.4844
#Mann= 3 , 0 , 0
9739.823   0.045       09739.823   0.045       010552.51   0.045       0
#XS Ineff= 2 , 0
       0                10156.73       0
Bank Sta=9739.823,10552.51
Exp/Cntr=0.3,0.1

Type RM Length L Ch R = 1 ,5150.626,164.352200,164.352200,164.352200
XS GIS Cut Line= 6
 1259540.5262354617012.2850385611259513.52845109616983.806050912
1259423.20202023616874.1915993541259372.81939191616828.448111191
1259277.29991895616795.9600730841258768.61936337616761.237850845
#Sta/Elev= 30
9787.997 83.21659817.50881.802639860.61178.761799877.62178.626519886.12677.78724
9958.37874.417759967.625 73.3137 9981.5973.2378910004.2670.82012 10021.672.47759
 10034.873.1095310059.2973.3472610132.0672.6701610171.8473.44189 10181.774.39751
10188.2874.1265810270.4975.0747510280.36 75.702910300.0975.6598210309.9575.05871
10323.1172.2645510336.26 71.781410346.13 72.639110369.1576.5681210385.5977.08727
10418.47 79.542610448.0777.99136 10553.378.7843210632.2280.6610410648.1380.22696
#Mann= 3 , 0 , 0
9787.997   0.045       09787.997   0.045       010648.13   0.045       0
#XS Ineff= 2 , 0
       0                10274.85       0
Bank Sta=9787.997,10648.13
Exp/Cntr=0.3,0.1

Type RM Length L Ch R = 1 ,4986.273,250.076500,250.076500,250.076500
XS GIS Cut Line= 6
1259860.86641255616772.2405090631259618.33781785616728.451224685
1259466.35826185616706.6611077491259464.40030104616706.253199279
1259360.18923008616692.5384528491258754.73047447616674.432295308
#Sta/Elev= 30
9599.01684.83452 9672.6382.772189762.64477.569419779.31478.010669859.24674.81969
9899.01872.497449922.21970.192559942.10570.131269981.87867.6157210001.7965.18571
10011.71 66.923710031.5768.3551210087.8269.5470110189.72 69.370310219.2670.81893
10245.5270.6511910255.3771.7749710271.7870.9592210301.3271.41453 10324.370.76518
10340.7168.0970510353.8467.7819810370.2569.5954510386.6672.8668110422.7773.94425
10439.1875.66351   10472 73.854210590.1675.0894210629.5576.2665210711.8476.58503
#Mann= 3 , 0 , 0
9599.016   0.045       09599.016   0.045       010711.84   0.045       0
#XS Ineff= 2 , 0
       0                10272.61       0
Bank Sta=9599.016,10711.84
Exp/Cntr=0.3,0.1

Type RM Length L Ch R = 1 ,4736.197,245.918800,245.918800,245.918800
XS GIS Cut Line= 6
1259794.66103002616521.6545175161259558.54991892616467.835073069
1259461.31694242616463.6894472841259385.12418368616473.067731813
1259331.56505206616483.2264487451258851.95269671616554.640628636
#Sta/Elev= 30
9594.63570.451439631.31669.858199661.60168.455219668.33167.603419718.80667.17339
9799.56663.56899 9866.1461.76749 9908.8361.84753 9954.9460.646629974.77461.33877
10001.2260.5473510017.8261.7182310074.4963.1831810091.0262.7298510104.2563.45943
10124.09 63.048610163.86 63.6492 10187.163.2564610203.6961.0322110220.2960.37903
10230.2461.1183210243.5263.9494310260.1266.2518510276.7166.7367710289.9967.94473
10313.2266.29624 10396.268.2417310492.4568.9979410525.6470.2967110550.3370.33888
#Mann= 3 , 0 , 0
9594.635   0.045       09594.635   0.045       010550.33   0.045       0
#XS Ineff= 2 , 0
       09836.035        10114.44       0
Bank Sta=9594.635,10550.33
Exp/Cntr=0.3,0.1

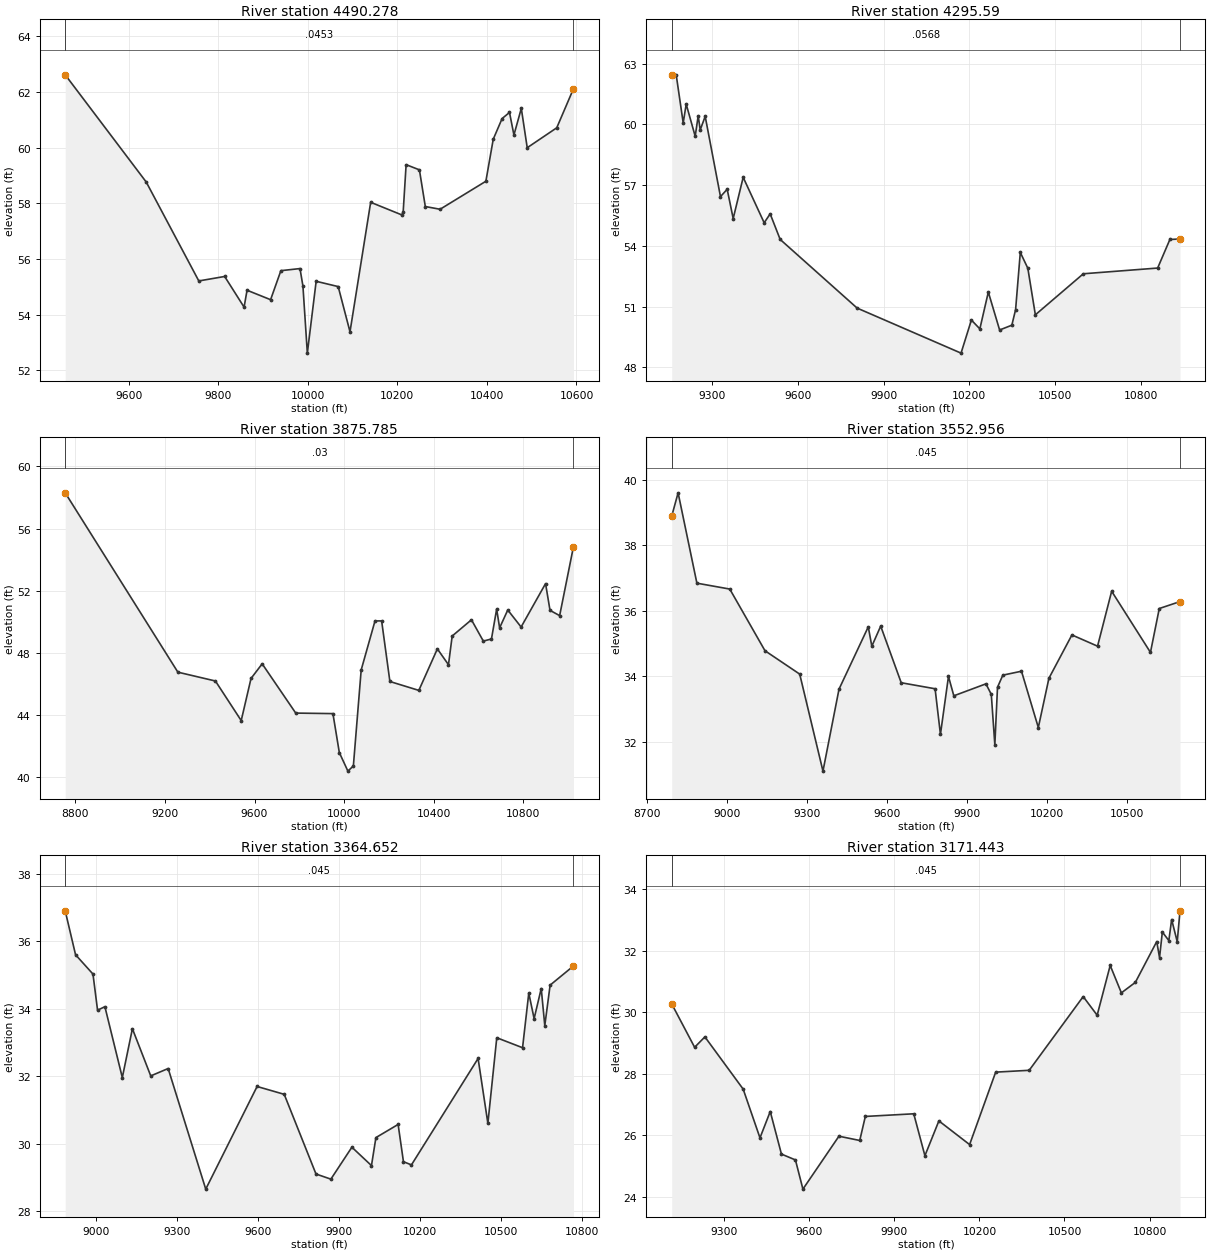
Type RM Length L Ch R = 1 ,4490.278,194.687900,194.687900,194.687900
XS GIS Cut Line= 6
1259884.93880779616361.9322953081259580.67064157616262.318443522
1259527.37505552616249.5128905181259487.89314193616244.514009789
1259287.71658561616250.8211841881258770.35547447616304.640628621
#Sta/Elev= 30
9458.06962.612269639.02458.761099756.479 55.20679814.22555.367689857.62254.26531
9864.23654.873059916.81954.533149939.79655.576119982.46855.651489989.03355.02578
9998.88152.6134610018.5855.1946310067.8155.0041110094.1753.3798310140.3558.03273
10209.6257.5809610212.92 57.675210219.5259.3845310249.2159.19815 10262.457.88011
10295.39 57.782310397.6458.7882210414.1360.2994910433.9261.0415210450.4261.26136
10460.3160.45081 10476.861.40573   1049059.9931910555.9760.7092810593.2762.11184
#Mann= 3 , 0 , 0
9458.069  0.0453       09458.069  0.0453       010593.27  0.0453       0
#XS Ineff= 2 , 0
       09847.206        10092.82       0
Bank Sta=9458.069,10593.27
Exp/Cntr=0.3,0.1

Type RM Length L Ch R = 1 , 4295.59,419.804900,419.804900,419.804900
XS GIS Cut Line= 4
1260154.09390041616348.4846679871259472.88822663  616094.1226888
1259211.16947666616005.5810221431258437.51403928616079.387445748
#Sta/Elev= 30
9157.59462.439089173.20162.449639197.71560.072679208.22161.00037 9239.7459.41528
9250.24760.429149257.25159.727999274.76160.39718  9328.356.432669351.807 56.7983
 9372.8255.349989407.84157.386499481.38555.141699502.39755.582789537.41854.31928
9807.07950.9277310171.0948.7033310207.3450.33724   10237  49.90110266.6751.71975
10306.2249.8459510349.0650.0829610362.24 50.852710378.7253.6769610405.0952.89468
10431.4550.5960410599.5352.62293 10859.952.9056210902.7454.31585 10938.254.34228
#Mann= 3 , 0 , 0
9157.594  0.0568       09157.594  0.0568       0 10938.2  0.0568       0
#XS Ineff= 2 , 0
       09896.063         10118.8       0
Bank Sta=9157.594,10938.2
Exp/Cntr=0.3,0.1

Type RM Length L Ch R = 1 ,3875.785,322.829100,322.829100,322.829100
XS GIS Cut Line= 6
1260149.75362262  616263.84925131259561.29100445615957.942133263
1259533.51322663615727.3865776961259412.77965903615615.389735579
1259209.90211555615881.5532443821258385.43070593615994.752029076
#Sta/Elev= 30
8754.11158.292939257.48546.765839425.20446.197939540.40943.654749584.29846.36275
9634.06247.302119784.02644.136039950.17944.102229978.72841.5989510017.0840.40543
10041.5140.7398510076.42 46.909210138.1750.0605710167.7850.0604610204.6846.16625
10333.9645.5942610416.7348.26255 10466.447.2449610482.9549.0893810569.0450.13266
10622.0148.7644210658.4348.8981310681.6150.8194510694.8549.6140410731.2750.76175
10790.8749.6683610900.1352.45923   1092050.7389110963.0450.4002611024.7354.82966
#Mann= 3 , 0 , 0
8754.111    0.03       08754.111    0.03       011024.73    0.03       0
#XS Ineff= 2 , 0
       09598.768        10115.17       0
Bank Sta=8754.111,11024.73
Exp/Cntr=0.3,0.1

Type RM Length L Ch R = 1 ,3552.956,188.303900,188.303900,188.303900
XS GIS Cut Line= 6
1260460.22454277615709.6138635871260210.22454277615612.391641349
1260036.61343163615556.8360857961259886.13282409615525.248536363
1259168.42797858615394.6980734021258602.39130232615321.407335803
#Sta/Elev= 30
8793.97138.894448817.78539.603018888.18936.843229011.39636.663169143.38534.77909
9273.48534.065159360.64631.101669420.78633.605819530.43135.509189543.72134.91695
9576.977 35.53159653.83733.801739780.82233.617599800.87132.22384 9830.9633.99462
9851.01933.402699971.37233.767939991.40333.4458810004.7231.9066510014.71 33.6639
10034.6834.0335110104.5934.1535910167.6632.4342710207.4333.9392810293.5935.26191
10389.6334.91885 10442.5 36.5966 10587.934.7284310620.9436.0686910698.6136.28074
#Mann= 3 , 0 , 0
8793.971   0.045       08793.971   0.045       010698.61   0.045       0
#XS Ineff= 2 , 0
       09539.226        10048.42       0
Bank Sta=8793.971,10698.61
Exp/Cntr=0.3,0.1

Type RM Length L Ch R = 1 ,3364.652,193.209700,193.209700,193.209700
XS GIS Cut Line= 6
1260478.34215912615549.0161555111259636.32827023615321.585599944
1259487.62466183615273.4913652091259417.17681101615264.361335695
 1259111.5118562615238.8804869061258636.08773759615192.900843993
#Sta/Elev= 30
8885.25836.905398923.61735.602148988.18735.029049005.17933.956959032.36634.06118
9096.93631.958359134.318 33.40729202.28632.007499266.85632.22629 9406.1928.64791
9596.501 31.69349697.07231.460819814.82729.096739869.99728.944279947.86229.89176
10020.4729.3460110036.9330.1770210119.2430.5671910138.9929.4620710168.6229.36672
10415.6832.5252810451.9430.59985 10484.933.1397110580.4932.8437110603.5634.46468
10623.3433.7068110649.7134.6007510662.8933.4988510682.6734.7007610769.1435.26874
#Mann= 3 , 0 , 0
8885.258   0.045       08885.258   0.045       010769.14   0.045       0
#XS Ineff= 2 , 0
       09615.789        10097.09       0
Bank Sta=8885.258,10769.14
Exp/Cntr=0.3,0.1

Type RM Length L Ch R = 1 ,3171.443,164.647500,164.647500,164.647500
XS GIS Cut Line= 3
1260377.34930548615155.0435266451259872.12195471615111.460649456
 1258587.7171591 615052.48837773
#Sta/Elev= 30
9114.71930.273769195.41328.865749231.63629.20407 9366.6527.506449425.92425.92268
9462.148  26.7799501.664 25.39619551.05925.205669577.40324.257769704.46425.97697
9777.86325.838329797.56826.619179968.35126.7051410007.7625.3437910057.0326.47457
10165.4125.7047710257.3728.05858 10375.628.1181210566.0930.5129510615.3629.90752
10661.3431.5241910700.7530.6339510750.0130.9737710825.55 32.3007 10835.431.77792
10845.2632.6102310868.2532.33297 10878.133.0157310897.81 32.295910907.5833.29898
#Mann= 3 , 0 , 0
9114.719   0.045       09114.719   0.045       010907.58   0.045       0
#XS Ineff= 2 , 0
       09803.353        10134.73       0
Bank Sta=9114.719,10907.58
Exp/Cntr=0.3,0.1

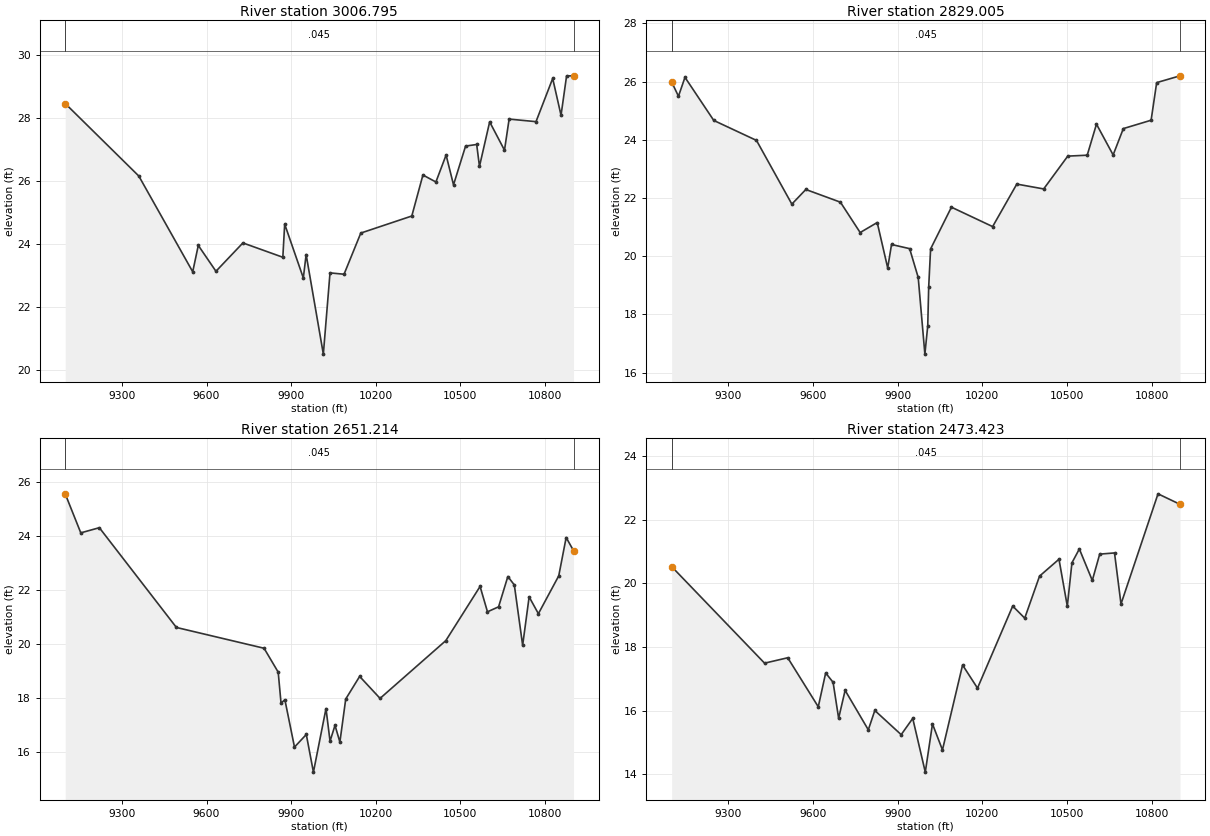
Type RM Length L Ch R = 1 ,3006.795,177.790500,177.790500,177.790500
XS GIS Cut Line= 6
 1260405.9805244615023.8833862351259595.94147543614953.309651572
1259543.21475508614945.1693466851259461.48995529614924.017578699
1259388.10565732614914.9828464541258612.28772105614871.339945952
#Sta/Elev= 30
9099.04528.46448 9359.9526.161129551.05723.118979570.82723.956499633.43123.13533
9728.95424.035829870.47123.580649877.05324.632359943.14222.923299953.10123.66769
10014.0820.5032810037.7123.0839410087.4923.0414910146.8724.3490710327.6724.89093
 10367.126.19356 10413.125.9718110449.2426.8285810475.5225.8808710518.2427.11173
10557.6627.1631810567.5226.4665110603.6627.8816510656.2326.9818810672.6627.96996
10767.9427.8882910827.0829.2598210856.6528.0909910876.3629.3442110900.9629.34208
#Mann= 3 , 0 , 0
9099.045   0.045       09099.045   0.045       010900.96   0.045       0
#XS Ineff= 2 , 0
       09819.775        10154.74       0
Bank Sta=9099.045,10900.96
Exp/Cntr=0.3,0.1

Type RM Length L Ch R = 1 ,2829.005,177.790600,177.790600,177.790600
XS GIS Cut Line= 6
 1260416.0885258614887.9282099281259856.54676498614832.320909124
1259448.09126424614742.5017649511259303.87563175 614719.61683703
1259091.71379395614703.9964706551258629.64795553614688.379820038
#Sta/Elev= 30
9099.02725.985359123.107 25.49679146.15826.146689248.24224.66523 9399.7223.97829
9525.05121.789289574.58722.292119697.19321.855629767.17620.812339827.66521.15575
9864.83219.595799878.34720.401219942.54420.258489972.953 19.26839996.60516.63302
10006.7517.6038910010.1318.9419710016.8920.2496510090.7121.6836810236.7821.01648
10322.4322.4772610417.7522.3108110503.1223.4388210572.0623.4702510604.8924.53789
10663.9723.4791610700.0824.3848910798.5724.6724310818.2625.9650910900.97 26.1985
#Mann= 3 , 0 , 0
9099.027   0.045       09099.027   0.045       010900.97   0.045       0
#XS Ineff= 2 , 0
       09817.365        10104.37       0
Bank Sta=9099.027,10900.97
Exp/Cntr=0.3,0.1

Type RM Length L Ch R = 1 ,2651.214,177.790600,177.790600,177.790600
XS GIS Cut Line= 6
1260499.67057093 614734.460160711259822.87631608614672.731385448
1259683.58322426614640.897748853 1259551.9781775614582.208201712
1259468.37091564614567.6285185771258718.98193807614550.653493378
#Sta/Elev= 30
9099.101  25.5519154.32224.104449220.10624.295549493.25620.598669803.92819.82813
 9854.0518.943359864.108 17.79489877.73317.920579911.79616.165329953.69216.63255
 9978.93 15.237410023.4817.5933110037.8216.3839810055.4116.9712510072.7116.35118
10093.4217.9464510142.7318.7842110215.1217.9702610448.2220.1108910569.6222.11841
10595.8621.1793710635.2421.3634310668.0522.4861110691.0122.1739910720.5419.93729
10743.5121.7324910776.3221.10895 10848.522.5119210874.7523.9323410900.89  23.445
#Mann= 3 , 0 , 0
9099.101   0.045       09099.101   0.045       010900.89   0.045       0
#XS Ineff= 2 , 0
       09881.253        10151.36       0
Bank Sta=9099.101,10900.89
Exp/Cntr=0.3,0.1

Type RM Length L Ch R = 1 ,2473.423,177.790600,177.790600,177.790600
XS GIS Cut Line= 6
1260465.11605748614404.9322232011259803.27310259 614388.04602716
1259671.96583639614406.3982755251259506.46991094614472.907933124
1259410.88380331614491.1291453731258680.33740994614498.592355249
#Sta/Elev= 30
9099.12520.528939428.39317.493239510.46817.663299618.74816.121649644.99617.18562
9671.24816.891999690.94215.761139713.91816.639099796.11515.397159819.18516.00562
9912.61515.245559953.60615.756729998.09814.0673510023.5615.5818110058.9414.76555
10130.2217.4346810183.1316.7085710307.9219.2886810350.57 18.908610403.07 20.2302
10471.9620.7612810501.4919.28459 10517.920.6489110544.14 21.083610590.0720.09427
10616.3220.9216510668.81  20.95910691.7819.3533210823.0122.8175810900.92 22.4877
#Mann= 3 , 0 , 0
9099.125   0.045       09099.125   0.045       010900.92   0.045       0
#XS Ineff= 2 , 0
       09791.311        10125.12       0
Bank Sta=9099.125,10900.92
Exp/Cntr=0.3,0.1