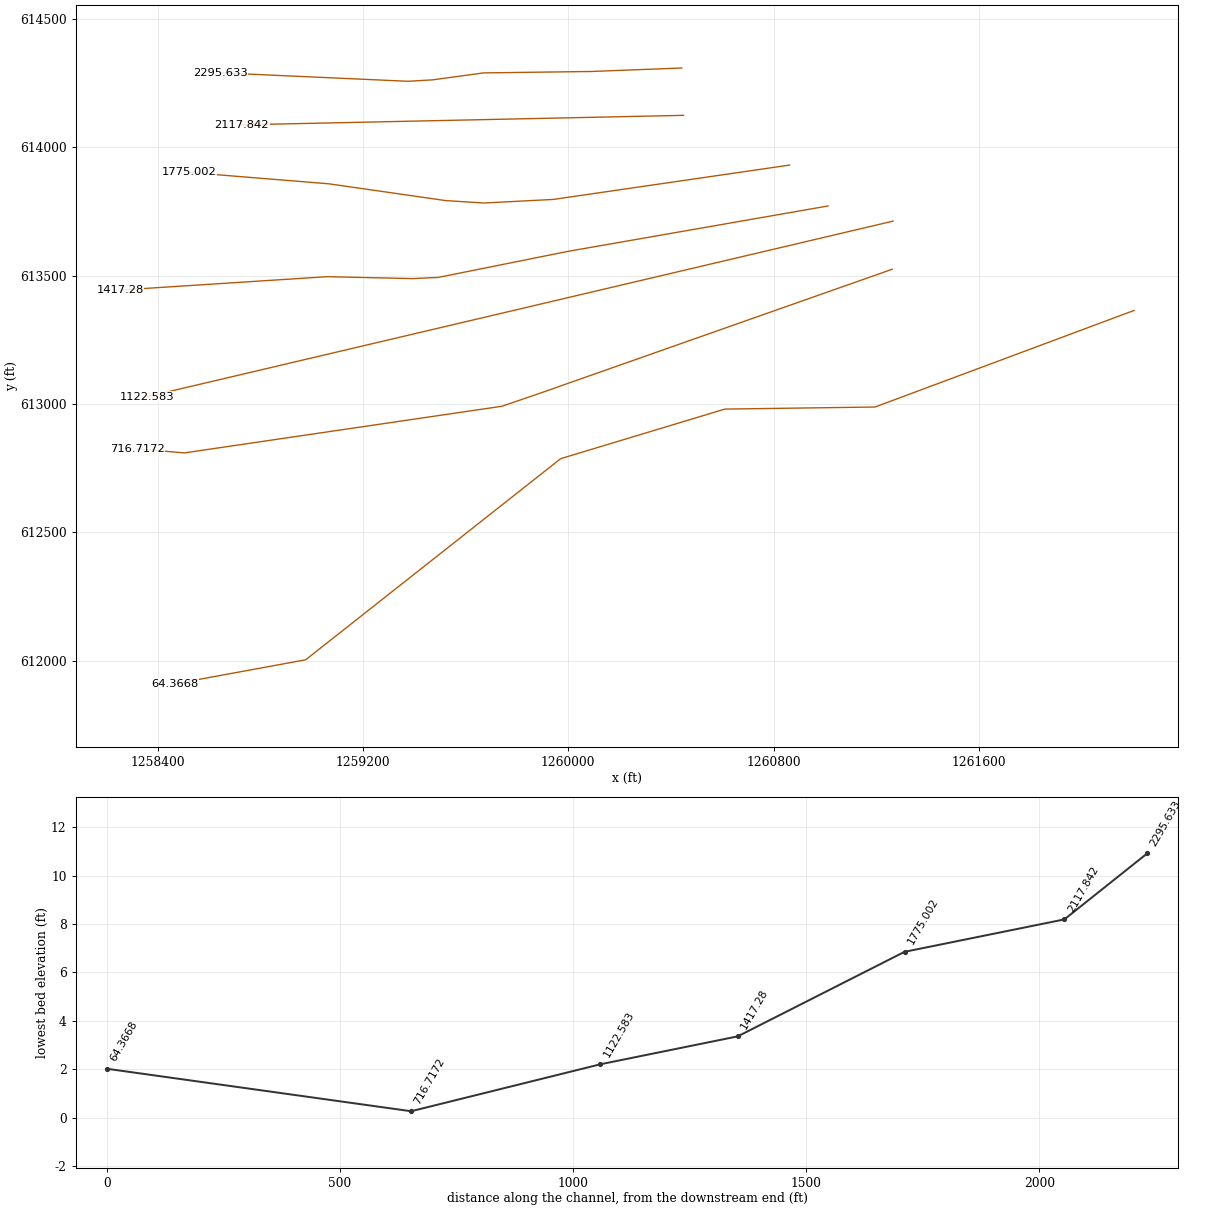
HEC-RAS study 481_ras.prj: 481

--- 481_ras.g01 (geometry) --- (continued)

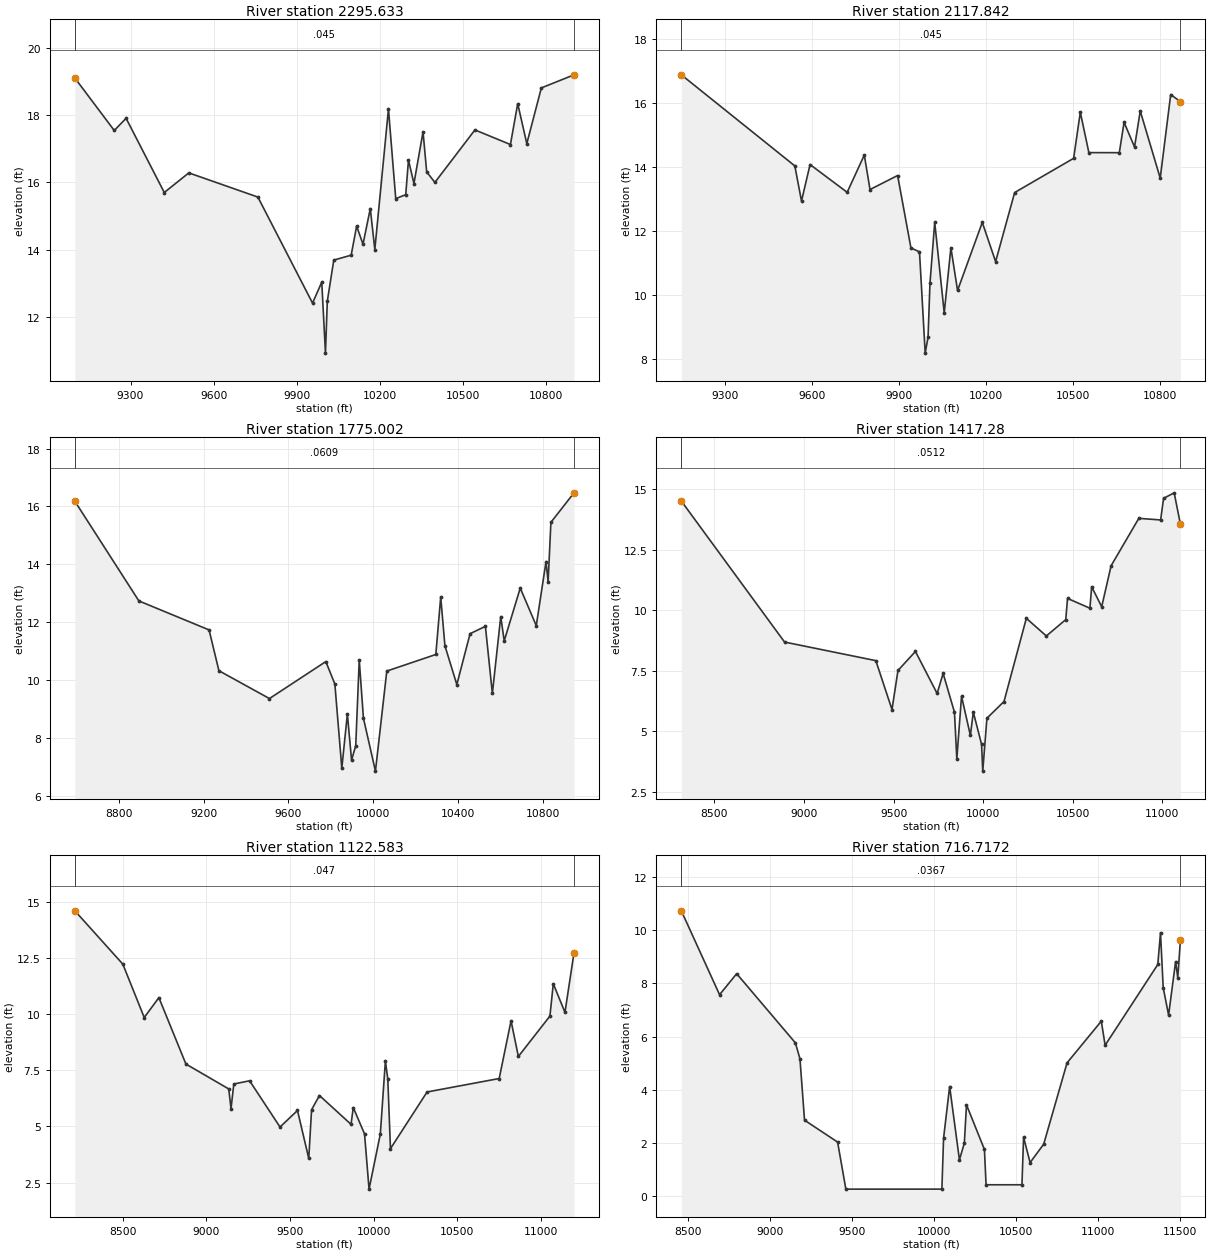
Type RM Length L Ch R = 1 ,2295.633,177.790600,177.790600,177.790600
XS GIS Cut Line= 6
1260442.29064537614308.8894828861260090.42739832614295.294534913
1259669.58403792614289.7419834331259471.43107996614262.654956058
1259374.96632649614257.0968056041258643.72224201614290.119790707
#Sta/Elev= 30
9099.045 19.11219241.24617.54883 9283.9417.912449421.80415.700369510.40316.28522
9759.75815.563859957.07612.404359990.38513.0290710003.7210.9128210010.3912.46015
10033.7313.6851610096.5213.8323710116.2814.6987610139.2614.1571510165.5215.22097
10181.9313.9998510231.1518.1878710257.4215.5181110293.5415.6354210303.3916.66616
10323.1115.9678410355.9817.5093210369.1316.3158210398.7116.0011210543.3217.56547
 10671.517.1301610697.7718.3484810730.5917.1571710783.1118.8176610900.9619.20774
#Mann= 3 , 0 , 0
9099.045   0.045       09099.045   0.045       010900.96   0.045       0
#XS Ineff= 2 , 0
       09772.751        10132.25       0
Bank Sta=9099.045,10900.96
Exp/Cntr=0.3,0.1

Type RM Length L Ch R = 1 ,2117.842,342.840100,342.840100,342.840100
XS GIS Cut Line= 2
1260448.79100442  614124.43518881258727.87086555614087.542827696
#Sta/Elev= 30
9150.38716.867649541.81514.026649564.78612.93076 9594.3214.069619722.30213.20352
9781.37114.36545 9801.0613.290199896.22613.727359942.16911.469789971.70311.34639
9991.3928.18790810001.248.681962 10007.810.3602810024.2112.2662310057.02 9.44229
   1008011.4760710102.9710.1417110188.29 12.264510234.2311.0416510299.8613.19623
10503.3214.2637510526.2915.7007710555.8314.4418210660.8414.4394610677.2415.38594
10713.3414.6167110733.0315.7385210801.9413.6454510838.0416.25294 10871.716.02851
#Mann= 3 , 0 , 0
9150.387   0.045       09150.387   0.045       0 10871.7   0.045       0
#XS Ineff= 2 , 0
       09810.766        10212.69       0
Bank Sta=9150.387,10871.7
Exp/Cntr=0.3,0.1

Type RM Length L Ch R = 1 ,1775.002,357.722400,357.722400,357.722400
XS GIS Cut Line= 6
1260861.90640038613930.7112304871259942.16366088613796.953843579
1259671.47894216613782.8955535441259521.80381954613792.427781656
1259066.76751152  613857.79456381258521.62862262613902.065397158
#Sta/Elev= 30
8591.08216.180678893.43412.733929224.96911.732149271.38410.321229510.0899.358722
9776.36910.637199819.0489.8617679851.8836.9521329878.1528.8234969897.8967.230272
9917.6927.7308359934.18910.69348 9954.068.67854210010.736.84943710064.3910.30927
10295.9210.8827710319.06 12.8712 10338.911.1837510395.12 9.8421810457.6911.60127
 10530.111.8556510563.029.53465610602.5212.1913910618.9811.3535610694.6913.17803
10770.3911.8788910816.4814.0956310826.3513.3963810839.5215.4508310948.5416.47202
#Mann= 3 , 0 , 0
8591.082  0.0609       08591.082  0.0609       010948.54  0.0609       0
#XS Ineff= 2 , 0
       0 9754.89        10082.09       0
Bank Sta=8591.082,10948.54
Exp/Cntr=0.3,0.1

Type RM Length L Ch R = 1 , 1417.28,294.696800,294.696800,294.696800
XS GIS Cut Line= 6
1261011.64598373613771.423036024 1260001.1851716613595.042279363
1259493.40215078 613493.144112141259394.24518427613488.423587516
1259060.92124376613495.9978180081258254.19202256613443.867302552
#Sta/Elev= 30
 8315.3514.505618891.4338.6870139400.7727.9199119490.9895.9013179524.4027.514154
9621.8448.2994879742.8866.5649939776.4087.3929339839.6065.7933259852.8423.868057
9879.1946.4504619928.4794.833056 9944.895.7934539990.9114.4683399997.5753.360199
10020.81 5.5443210116.12 6.2325610240.829.66622410352.468.93813610460.85 9.61339
10470.7110.48768 10595.610.0831910605.4610.9687510661.3410.1443110713.9611.83756
10868.5813.79235 10990.313.7261611006.7414.6184511065.9614.8455311100.9513.53869
#Mann= 3 , 0 , 0
 8315.35  0.0512       0 8315.35  0.0512       011100.95  0.0512       0
#XS Ineff= 2 , 0
       09624.288        10147.75       0
Bank Sta=8315.35,11100.95
Exp/Cntr=0.3,0.1

Type RM Length L Ch R = 1 ,1122.583,405.865700,405.865700,405.865700
XS GIS Cut Line= 2
1261265.11820596613712.3952582631258358.86820596613028.367480472
#Sta/Elev= 30
8213.11814.615358499.93612.239068628.0159.8589688715.647 10.7453 8877.437.783538
9133.5876.6741489147.0695.7971879163.9216.8938379258.2957.0379589440.3014.976426
9544.7865.7130569612.1953.5756149629.0485.7477169676.2356.3813679864.9825.096692
9878.4635.8436299945.873 4.669539972.8372.20714910040.254.65990710070.587.919842
10085.057.10963510100.92 4.01232   103206.53873410751.427.138949 10822.29.710943
10866.018.12162511054.769.92263411074.9811.3622111144.7510.0878411198.7812.73909
#Mann= 3 , 0 , 0
8213.118   0.047       08213.118   0.047       011198.78   0.047       0
#XS Ineff= 2 , 0
       09683.724        10323.79       0
Bank Sta=8213.118,11198.78
Exp/Cntr=0.3,0.1

Type RM Length L Ch R = 1 ,716.7172,652.350400,652.350400,652.350400
XS GIS Cut Line= 5
1261261.64598373613524.8952582481259893.67723376613043.363140211
1259741.76751149612991.2798068821258504.26931995 612809.53483434
1258321.97765329 612825.15983434
#Sta/Elev= 30
8456.41410.730018689.5867.577328 8793.93 8.367019152.181 5.765929180.0065.167037
9207.8312.8608449409.565 2.037799460.0180.26902910045.670.26902910056.082.187001
10093.044.12514610152.73 1.3716910182.581.99464410195.843.43768810305.27 1.75934
10315.220.43307110534.080.43307110544.022.22041510583.821.26674310666.721.958913
10809.315.01622611018.226.58236411041.435.67671911362.778.71272211379.239.908722
 11395.77.84511311428.636.81037611471.43 8.82372 11484.68.22103511500.98 9.64425
#Mann= 3 , 0 , 0
8456.414  0.0367       08456.414  0.0367       011500.98  0.0367       0
#XS Ineff= 2 , 0
       09826.638        10439.67       0
Bank Sta=8456.414,11500.98
Exp/Cntr=0.3,0.1

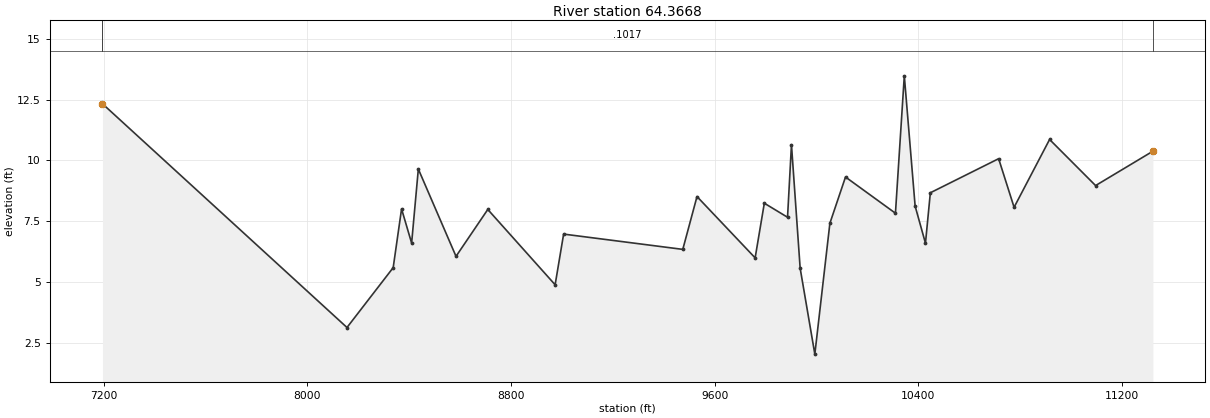
Type RM Length L Ch R = 1 , 64.3668,0.000000,0.000000,0.000000
XS GIS Cut Line= 6
1262204.03660357613364.5543499441261194.86369678612988.275806516
 1260609.8230671612980.2120985241259970.49239331612787.195605487
1258977.01056707612003.649598539 1258469.0614776611910.424340948
#Sta/Elev= 30
7195.42312.330558155.8073.1178588337.2465.5825668370.1588.0000288409.6536.594383
8435.9839.640927 8583.986.0478018708.755  7.97818973.2194.8774569006.5726.963847
9474.5436.3346629530.3538.5096819758.6935.9849579794.747 8.235659885.9167.657103
9901.33610.645579935.4615.5581489993.1052.021831 10052.27.40864810113.569.314573
10309.677.82331310344.4713.4803610386.988.11676410427.576.58803110446.728.665193
10714.9310.0683510775.638.06776410915.0410.8598311095.658.96188511320.7210.37634
#Mann= 3 , 0 , 0
7195.423  0.1017       07195.423  0.1017       011320.72  0.1017       0
#XS Ineff= 2 , 0
       09894.025        10039.92       0
Bank Sta=7195.423,11320.72
Exp/Cntr=0.3,0.1